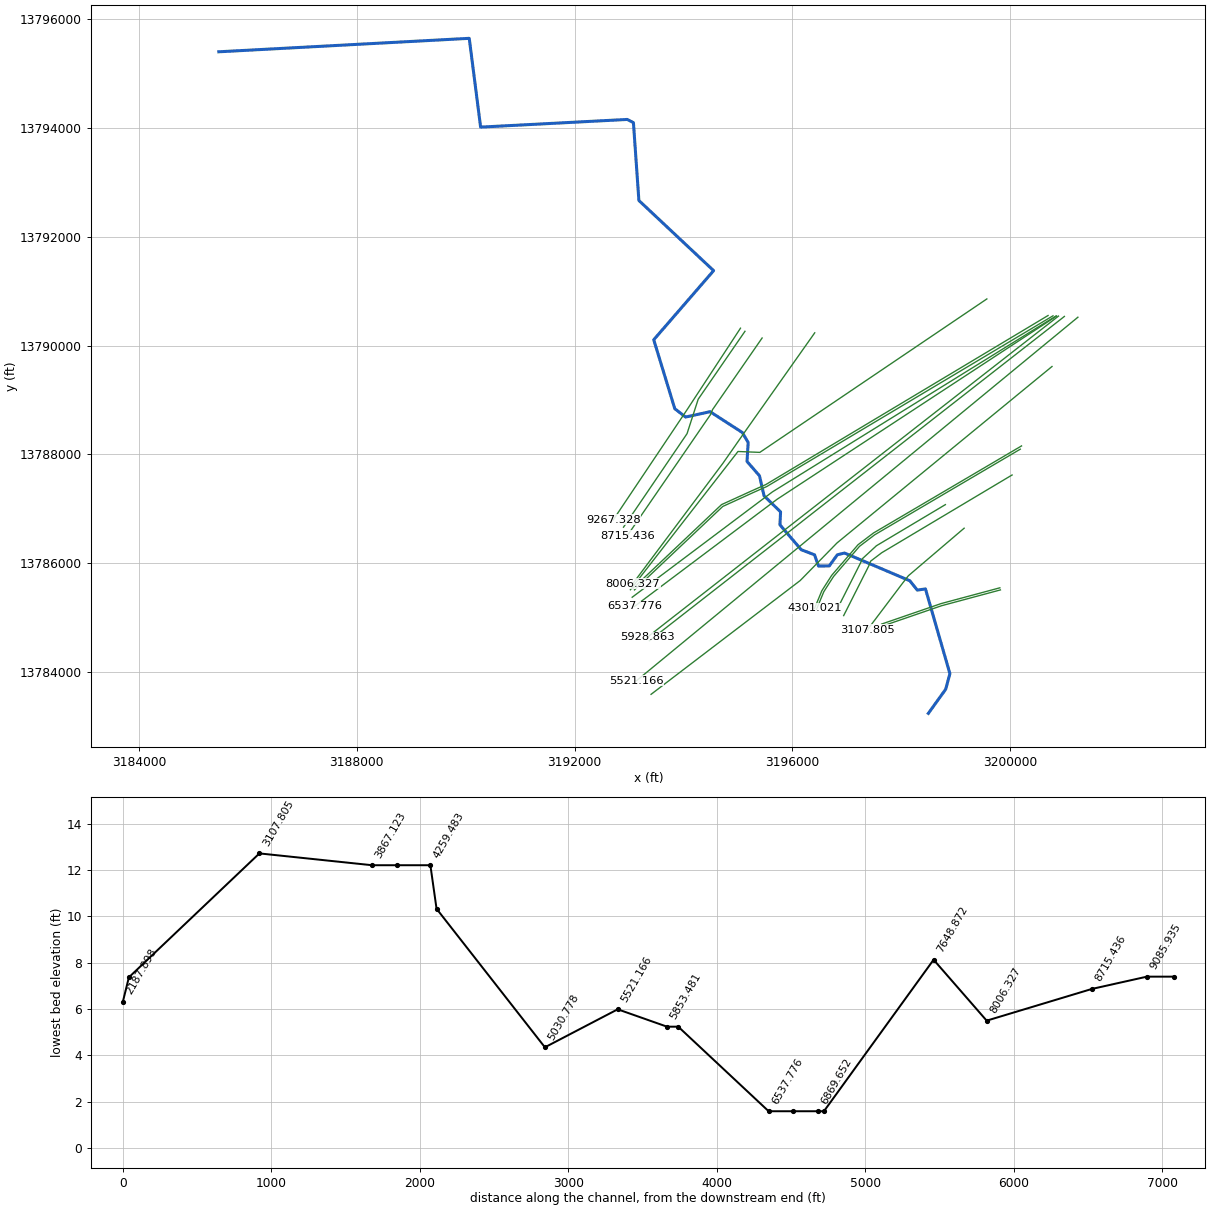
--- B104_04_00.prj (project) ---

Proj Title=B104-04-00
Current Plan=p02
Default Exp/Contr=.3,.1
English Units
Geom File=g01
Geom File=g02
Flow File=f01
Flow File=f02
Plan File=p01
Plan File=p02
Y Axis Title=Elevation
X Axis Title(PF)=Main Channel Distance
X Axis Title(XS)=Station
BEGIN DESCRIPTION:
Armand Bayou
Horsepen Bayou Tributary 4.51
HCFCD Unit B104-04-00
Flood Hazard Model
10, 2, 1, 0.2% Event
Filename B140_04_00.prj
Prepared by: Christopher Moss Date: 6/15/2004
Reviewd by:		Date:
Status FINAL
END DESCRIPTION:
DSS File=dss
DSS Export Rating Curves= 0
DSS Export Rating Curve Sorted= 0
DSS Export Volume Flow Curves= 0
DXF OffsetX= 0
DXF OffsetY= 0
DXF ScaleX= 1
DXF ScaleY= 10

--- B104_04_00.p02 (plan) ---

Plan Title=Floodway
Version=Version 3.0.1  Mar 2001
Short Identifier=Floodway0607
Geom File=g02
Flow File=f02
Subcritical Flow
K Sum by GR= 0
Std Step Tol= 0.01
Critical Tol= 0.01
Num of Std Step Trials= 20
Max Error Tol= 0.3
Flow Tol Ratio= 0.001
Split Flow NTrial= 30
Split Flow Tol= 0.02
Split Flow Ratio= 0.02
Log Output Level= 0
Friction Slope Method= 0
Unsteady Friction Slope Method= 2
Secant Critical Depth
Global Vel Dist= 0 , 0 , 0
Global Log Level= 0
CheckData=True
Encroach Param=-1 ,0,0, 2
Encroach River=B104-04-00
Encroach Reach=MAIN
Encroach Node=9267.328
       1 1864.04 1977.57
Encroach Node=9085.935
       1  4950.7    5031
Encroach Node=8715.436
       1  4940.7  5039.3
Encroach Node=8360.88
       1 4622.17 5428.35
Encroach Node=8006.327
       1 4622.17 5428.35
Encroach Node=7648.872
       1 4545.03 5454.97
Encroach Node=6910.224
       1 4696.84 5286.59
Encroach Node=6869.652
       1  4751.4  5248.6
Encroach Node=6784.331
       1  4751.4  5248.6
Encroach Node=6699.01
       1 4769.14 5255.29
Encroach Node=6537.776
       1    4769    5231
Encroach Node=5928.863
       1 4637.91 5374.79
Encroach Node=5853.481
       1 4633.76 5366.24
Encroach Node=5687.32
       1 4633.76 5366.24
Encroach Node=5521.166
       1 4482.76 5517.25
Encroach Node=5030.778
       1 4460.98 5539.02
Encroach Node=4301.021
       1 4832.26 5167.74
Encroach Node=4259.483
       1  4892.5 5114.15
Encroach Node=4145.833
       1  4892.5 5114.15
Encroach Node=4032.183
       1 4893.94 5180.92
Encroach Node=3867.123
       1 4901.41 5088.94
Encroach Node=3107.805
       1 4862.58 5137.42
Encroach Node=2228.678
       1 4928.27 5071.73
Encroach Node=2187.898
       1  4874.4 5067.19
Encroach Node=2113.24
       1  4874.4 5067.19
Encroach Node=2038.573
       1 4864.12 5135.88
Encroach Node=1869.963
       1 4930.73 5085.44
Encroach Node=834.987
       1 4887.35 5159.06
Encroach Node=810.101
       1 4916.41 5083.59
Encroach Node=721.302
       1 4888.89 5154.36
Encroach Node=632.503
       1 4888.89 5154.36
Encroach Node=551.743
       1 4908.42 5091.59
Encroach Node=354.034
       1 4840.91 5106.12
Encroach Node=328.901
       1 4845.91 5133.99
Encroach Node=247.943
       1 4845.91 5133.99
Encroach Node=166.985
       1 4909.72 5090.29
Encroach Node=83.687
       1 4903.22 5096.79
Encroach Reach=B104-04-00_0001
Encroach Node=9267.328
       1 1864.04 1977.57
Encroach Node=9085.935
       1  4950.7    5031
Encroach Node=8715.436
       1  4940.7  5039.3
Encroach Node=8360.88
       1 4622.17 5428.35
Encroach Node=8006.327
       1 4622.17 5428.35
Encroach Node=7648.872
       1 4545.03 5454.97
Encroach Node=6910.224
       1 4696.84 5286.59
Encroach Node=6869.652
       1  4751.4  5248.6
Encroach Node=6784.331
       1  4751.4  5248.6
Encroach Node=6699.01
       1 4769.14 5255.29
Encroach Node=6537.776
       1    4769    5231
Encroach Node=5928.863
       1 4637.91 5374.79
Encroach Node=5853.481
       1 4633.76 5366.24
Encroach Node=5687.32
       1 4633.76 5366.24
Encroach Node=5521.166
       1 4482.76 5517.25
Encroach Node=5030.778
       1 4460.98 5539.02
Encroach Node=4301.021
       1 4832.26 5167.74
Encroach Node=4259.483
       1  4892.5 5114.15
Encroach Node=4145.833
       1  4892.5 5114.15
Encroach Node=4032.183
       1 4893.94 5180.92
Encroach Node=3867.123
       1 4901.41 5088.94
Encroach Node=3107.805
       1 4862.58 5137.42
Encroach Node=2228.678
       1 4928.27 5071.73
Encroach Node=2187.898
       1  4874.4 5067.19
Encroach Node=2113.24
       1  4874.4 5067.19
Encroach Node=2038.573
       1 4864.12 5135.88
Encroach Node=1869.963
       1 4930.73 5085.44
Encroach Node=834.987
       1 4887.35 5159.06
Encroach Node=810.101
       1 4916.41 5083.59
Encroach Node=721.302
       1 4888.89 5154.36
Encroach Node=632.503
       1 4888.89 5154.36
Encroach Node=551.743
       1 4908.42 5091.59
Encroach Node=354.034
       1 4840.91 5106.12
Encroach Node=328.901
       1 4845.91 5133.99
Encroach Node=247.943
       1 4845.91 5133.99
Encroach Node=166.985
       1 4909.72 5090.29
Encroach Node=83.687
       1 4903.22 5096.79
Computation Interval=1HOUR
Output Interval=1HOUR
Run HTab= 0
Run UNet= 0
Run PostProcess= 0
UNET Theta= 1
UNET ZTol= 0.02
UNET ZSATol= 0.1
UNET MxIter= 20
UNET MaxInSteps= 20
UNET DtIC= 0
UNET DtMin= 0
UNET MaxCRTS= 20
UNET WFStab= 2
UNET SFStab= 1
UNET WFX= 1
UNET SFX= 1
UNET Convert EG Bridges=-1
UNET Use Existing IB Tables=-1
Instantaneous Interval=1HOUR
Write IC File= 0
IC Time=0
Write Velocity= 0
Write Detailed= 0

--- B104_04_00.p01 (plan) ---

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Plan Title=FEMA Effective June 2007
Short Identifier=FEMAeff0607
Geom File=g01
Flow File=f01
Encroach Param=-1 ,0,0, 0
DSS File=dss

--- B104_04_00.f02 (steady flow) ---

Flow Title=Floodway
Version=Version 3.0.1  Mar 2001
Number of Profiles= 2
Profile Names=1PCT_100yr, 1PCTFloodway_100yrFW
River Rch & RM=B104-04-00,B104-04-00_0001            ,9267.328
     799     799
River Rch & RM=B104-04-00,B104-04-00_0001            ,9085.935
     799     799
River Rch & RM=B104-04-00,B104-04-00_0001            ,8715.436
     863     863
River Rch & RM=B104-04-00,B104-04-00_0001            ,8006.327
     898     898
River Rch & RM=B104-04-00,B104-04-00_0001            ,7648.872
     974     974
River Rch & RM=B104-04-00,B104-04-00_0001            ,6910.224
    1014    1014
River Rch & RM=B104-04-00,B104-04-00_0001            ,6537.776
    1084    1084
River Rch & RM=B104-04-00,B104-04-00_0001            ,5928.863
    1134    1134
River Rch & RM=B104-04-00,B104-04-00_0001            ,5521.166
    1196    1196
River Rch & RM=B104-04-00,B104-04-00_0001            ,5030.778
    1196    1196
River Rch & RM=B104-04-00,B104-04-00_0001            ,4301.021
     211     211
River Rch & RM=B104-04-00,B104-04-00_0001            ,4259.483
     224     224
River Rch & RM=B104-04-00,B104-04-00_0001            ,4032.183
     234     234
River Rch & RM=B104-04-00,B104-04-00_0001            ,3867.123
     287     287
River Rch & RM=B104-04-00,B104-04-00_0001            ,3107.805
     362     362
River Rch & RM=B104-04-00,B104-04-00_0001            ,2228.678
     366     366
River Rch & RM=B104-04-00,B104-04-00_0001            ,2187.898
     381     381
River Rch & RM=B104-04-00,B104-04-00_0001            ,2038.573
     398     398
River Rch & RM=B104-04-00,B104-04-00_0001            ,1869.963
     525     525
River Rch & RM=B104-04-00,B104-04-00_0001            ,834.987
     528     528
River Rch & RM=B104-04-00,B104-04-00_0001            ,810.101
     554     554
River Rch & RM=B104-04-00,B104-04-00_0001            ,632.503
     566     566
River Rch & RM=B104-04-00,B104-04-00_0001            ,551.743
     597     597
River Rch & RM=B104-04-00,B104-04-00_0001            ,354.034
     601     601
River Rch & RM=B104-04-00,B104-04-00_0001            ,328.901
     627     627
River Rch & RM=B104-04-00,B104-04-00_0001            ,166.985
     641     641
Boundary for River Rch & Prof#=B104-04-00,B104-04-00_0001            , 1
Up Type= 0
Dn Type= 3
Dn Slope=.0003
Boundary for River Rch & Prof#=B104-04-00,B104-04-00_0001            , 2
Up Type= 0
Dn Type= 3
Dn Slope=.0003
DSS Import GetInterval= 0
DSS Import GetPeak= 0
DSS Import FillOption= 0

--- B104_04_00.f01 (steady flow) ---

Flow Title=FEMA Effective June 2007
Program Version=3.11
Number of Profiles= 4
Profile Names=10PCT_10yr, 2PCT_50yr, 1PCT_100yr, 0.2PCT_500yr
River Rch & RM=B104-04-00,B104-04-00_0001            ,9267.328
     422     588     799    1585
River Rch & RM=B104-04-00,B104-04-00_0001            ,9085.935
     422     588     799    1585
River Rch & RM=B104-04-00,B104-04-00_0001            ,8715.436
     464     654     863    1608
River Rch & RM=B104-04-00,B104-04-00_0001            ,8006.327
     487     690     898    1620
River Rch & RM=B104-04-00,B104-04-00_0001            ,7648.872
     537     771     974    1644
River Rch & RM=B104-04-00,B104-04-00_0001            ,6910.224
     564     816    1014    1656
River Rch & RM=B104-04-00,B104-04-00_0001            ,6537.776
     612     894    1084    1676
River Rch & RM=B104-04-00,B104-04-00_0001            ,5928.863
     646     950    1134    1690
River Rch & RM=B104-04-00,B104-04-00_0001            ,5521.166
     690    1023    1196    1707
River Rch & RM=B104-04-00,B104-04-00_0001            ,5030.778
     690    1023    1196    1707
River Rch & RM=B104-04-00,B104-04-00_0001            ,4301.021
      54     164     211     304
River Rch & RM=B104-04-00,B104-04-00_0001            ,4259.483
      59     175     224     322
River Rch & RM=B104-04-00,B104-04-00_0001            ,4032.183
      63     183     234     336
River Rch & RM=B104-04-00,B104-04-00_0001            ,3867.123
      87     227     287     411
River Rch & RM=B104-04-00,B104-04-00_0001            ,3107.805
     126     291     362     518
River Rch & RM=B104-04-00,B104-04-00_0001            ,2228.678
     128     294     366     523
River Rch & RM=B104-04-00,B104-04-00_0001            ,2187.898
     136     307     381     544
River Rch & RM=B104-04-00,B104-04-00_0001            ,2038.573
     147     322     398     569
River Rch & RM=B104-04-00,B104-04-00_0001            ,1869.963
     227     430     525     747
River Rch & RM=B104-04-00,B104-04-00_0001            ,834.987
     229     434     528     752
River Rch & RM=B104-04-00,B104-04-00_0001            ,810.101
     247     456     554     788
River Rch & RM=B104-04-00,B104-04-00_0001            ,632.503
     255     466     566     805
River Rch & RM=B104-04-00,B104-04-00_0001            ,551.743
     278     493     597     847
River Rch & RM=B104-04-00,B104-04-00_0001            ,354.034
     281     497     601     853
River Rch & RM=B104-04-00,B104-04-00_0001            ,328.901
     300     520     627     890
River Rch & RM=B104-04-00,B104-04-00_0001            ,166.985
     311     532     641     910
Boundary for River Rch & Prof#=B104-04-00,B104-04-00_0001            , 1
Up Type= 0
Dn Type= 3
Dn Slope=0.0003
DSS Import GetInterval= 0
DSS Import GetPeak= 0
DSS Import FillOption= 0

--- B104_04_00.g02 (geometry) ---

Geom Title=B104-04-00 June 2007 (Floodway)
Program Version=3.11

River Reach=B104-04-00      ,B104-04-00_0001
Reach XY= 30
      3185468.25       13795393.        3190066.       13795640.
      3190274.75       13794010.        3192967.       13794151.
      3193080.25       13794092.       3193180.5       13792663.
      3194552.25       13791375.     3193453.048    13790106.315
     3193839.591    13788839.879     3194038.069    13788687.513
     3194487.856    13788785.502     3195080.597    13788402.475
     3195187.405    13788219.375       3195165.5       13787872.
      3195394.75       13787609.      3195478.25       13787241.
       3195781.5       13786946.      3195770.25       13786708.
       3196161.5       13786251.      3196405.25       13786158.
      3196477.25       13785952.        3196676.       13785954.
      3196823.69    13786158.618     3196956.571    13786190.964
     3198155.122    13785681.296       3198291.5    13785510.824
     3198441.866    13785531.805     3198890.339    13783975.699
      3198813.25       13783690.       3198494.5       13783247.

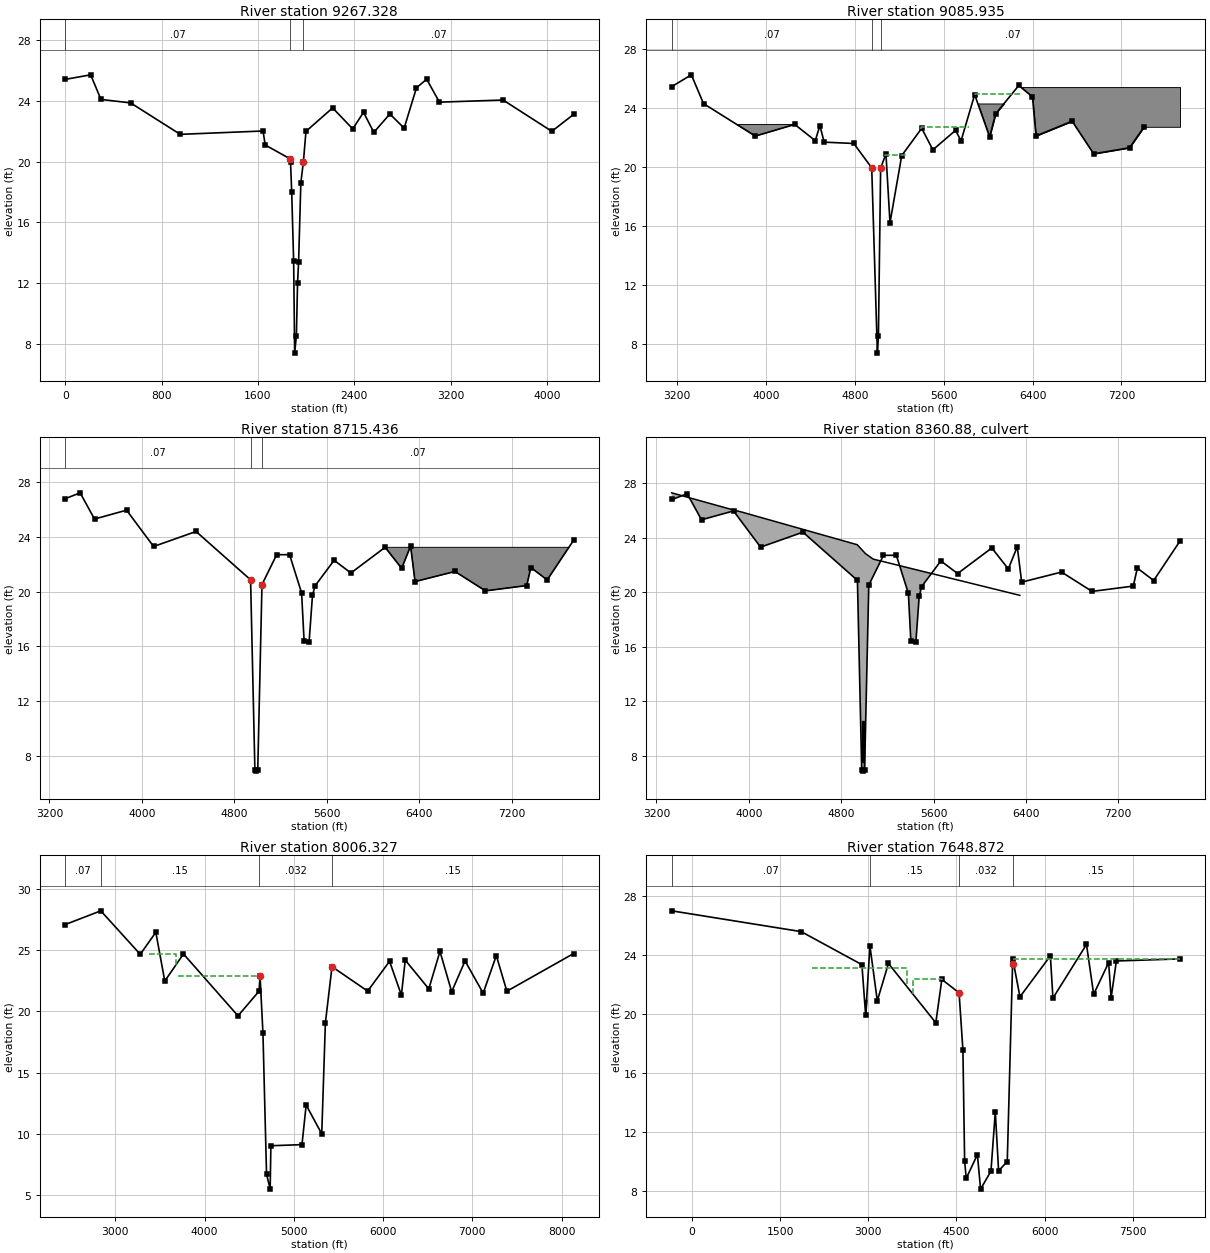
Type RM Length L Ch R = 1 ,9267.328,156.77,181.39,235.61
XS GIS Cut Line= 3
     3195045.719    13790318.586     3194065.797    13788823.331
      3192711.58     13786802.53
#Sta/Elev= 30
       0   25.42  211.35   25.72  296.63    24.1  543.09   23.87  955.06    21.8
 1642.36   22.02 1660.61    21.1 1864.04    20.2 1870.48      20 1880.45      18
 1896.63   13.43 1904.92    7.39 1919.39    8.54 1929.04      12 1937.78    13.4
 1956.34    18.6 1977.57      20 1998.98      22 2220.24   23.54 2387.09   22.16
 2476.77   23.25 2562.29   21.93 2695.49   23.14 2814.02   22.21 2916.51   24.87
 3001.28   25.43 3106.79   23.92 3635.36   24.06 4040.09      22 4220.35   23.11
#Mann= 3 , 0 , 0
       0     .07       0 1864.04    .032       0 1977.57     .07       0
Bank Sta=1864.04,1977.57
XS Rating Curve= 0
Exp/Cntr=0.3,0.1

Type RM Length L Ch R = 1 ,9085.935,381.91,370.5,301.16
XS GIS Cut Line= 4
     3195128.084    13790261.876      3194269.09      13789014.3
     3194064.496    13788381.918     3192897.822    13786665.327
#Sta/Elev= 30
 3149.16   25.44 3326.43   26.24 3436.05   24.29 3902.51   22.09 4257.51   22.88
 4442.33   21.78 4483.93    22.8 4522.76   21.68 4789.38   21.59  4950.7   19.94
 5001.69    7.39 5010.95    8.54    5031   19.94    5079   20.88 5115.23   16.22
 5220.91   20.77 5400.94   22.62 5501.44   21.16 5705.66   22.48 5755.29   21.77
 5877.79    24.9 6012.49   22.04 6066.77    23.6  6275.5   25.52 6398.51   24.75
 6430.11    22.1  6755.6    23.1 6949.21   20.89 7272.71    21.3 7404.04   22.72
#Mann= 3 , 0 , 0
 3149.16     .07       0  4950.7    .032       0    5031     .07       0
#XS Ineff= 3 ,-1
 5878.27  6299.2   24.94 5394.77 5827.08   22.72 5070.53 5269.62   20.82
Permanent Ineff=
       F       F       F
#Block Obstruct= 3 ,-1
 3506.26 4268.49   22.88 5906.71 6230.94    24.3 6282.14 7726.96   25.41
Bank Sta=4950.7,5031
XS Rating Curve= 0
Exp/Cntr=0.5,0.3

Type RM Length L Ch R = 1 ,8715.436,721.78,709.11,1100.45
XS GIS Cut Line= 4
     3195442.932    13790138.695     3194532.569    13788823.571
     3194495.315     13788732.28     3192966.445    13786507.255
#Sta/Elev= 30
 3336.91   26.81 3466.07   27.24 3590.36   25.32  3867.7   25.97 4101.96   23.31
 4468.82   24.41  4940.7   20.87 4977.94    6.95 4990.86    6.86  5002.7    6.95
  5039.3   20.52  5166.3   22.71 5278.02   22.71 5382.05   19.91 5403.62   16.39
 5446.77   16.31 5476.24   19.74 5497.99   20.42 5663.19    22.3  5808.6   21.37
  6104.6   23.25 6247.82   21.71 6325.17   23.34 6363.44   20.74  6708.9   21.48
 6972.94   20.06 7329.85   20.45 7365.36   21.77 7506.62   20.86 7734.64   23.76
#Mann= 3 , 0 , 0
 3336.91     .07       0  4940.7    .032       0  5039.3     .07       0
#Block Obstruct= 1 ,-1
 6111.49 8113.77   23.25
Bank Sta=4940.7,5039.3
XS Rating Curve= 0
Exp/Cntr=0.5,0.3

Type RM Length L Ch R = 2 ,8360.88 ,,,
Node Photo=G:\C2001-041_Harris_County_FEMA\1-Armand_Bayou\Horsepen_Bayou_Trib_4.51\Survey info\3113S01\311301P04.JPG
BEGIN DESCRIPTION:
Space Center Boulevard
END DESCRIPTION:
Bridge Culvert--1,0,-1,-1, 0
Deck Dist Width WeirC Skew NumUp NumDn MinLoCord MaxHiCord MaxSubmerge Is_Ogee
69.058,570.793,2.6,0, 7, 7, , , 0.95, 0, 0,0,,
    3332    3820 3942.43 4938.94    5011 5077.95  6347.6
    27.3   26.15   25.88   23.49   22.83   22.43   19.77
       0       0       0       0       0       0       0
    2430    3520 3642.43 4638.94    4711 4777.95  6047.6
    28.3   26.15   25.88   23.49   22.83   22.43   19.77
               0       0       0       0       0       0
BR Coef=-1 , 0 , 0 ,, 0 ,,,0.8,0,,0,
WSPro=,,,, 1 ,,,, 0 ,,,, 0 ,,,,-1 ,-1 ,-1 , 0 , 0 , 0 , 0 , 0
Multiple Barrel Culv=2,3,6,570.793,0.012,0.5,1,10,1,7.5541,6.9766, 2,Culvert #1  , 0 ,69.058
    4984    4710    4991    4717
Culvert Bottom n=0.012
Culvert=2,3,6,570.793,0.012,0.5,1,10,1,7.0541,4998,6.4766,4724,Culvert #2  , 0 ,69.058
Culvert Bottom n=0.012
BC Design=,, 0 ,, 0 ,,,,,,
BC HTab HWMax=27

Type RM Length L Ch R = 1 ,8006.327,567.1,357.45,85.84
XS GIS Cut Line= 4
     3196408.632    13790233.444     3195156.591    13788459.668
     3194724.181    13787839.963     3193065.929    13785624.735
#Sta/Elev= 30
 2439.72   27.08  2838.3    28.2 3280.52   24.65 3454.56   26.45 3555.13   22.47
 3764.59   24.68 4375.04   19.63 4610.87   21.64 4622.17   22.91 4654.77   18.19
  4694.9    6.72  4735.6    5.49 4743.45    9.03  5091.8    9.12 5138.79   12.35
 5313.34      10 5354.04   19.06 5428.35   23.64 5827.55   21.65 6072.78   24.08
  6205.5   21.32 6248.63   24.18 6512.54   21.83 6637.51   24.89 6768.64    21.6
 6918.54   24.11 7121.47   21.48 7268.77   24.55 7386.96   21.64 8133.66   24.71
#Mann= 4 ,-1 , 0
 2439.72     .07       0  2838.3     .15       0 4610.87    .032       0
 5428.35     .15       0
#XS Ineff= 3 ,-1
  3377.7 3680.32   24.67 3704.25 4623.28    22.9 5432.31 8133.66   23.57
Permanent Ineff=
       F       F       F
Bank Sta=4622.17,5428.35
XS Rating Curve= 0
Exp/Cntr=0.5,0.3

Type RM Length L Ch R = 1 ,7648.872,585.91,738.65,642.44
XS GIS Cut Line= 4
     3199568.798    13790855.664     3195400.736    13788038.678
     3194999.836    13788054.975     3193024.545    13785516.671
#Sta/Elev= 30
 -344.76   26.99  1858.7   25.58 2891.72   23.34 2955.55    19.9 3028.07   24.62
 3153.55   20.89 3343.25   23.42 4148.98    19.4 4251.86   22.34 4545.03   21.43
 4610.26   17.55 4639.38   10.02 4666.68    8.85 4856.64   10.46 4910.94    8.12
 5087.19    9.34 5161.21   13.36 5217.38    9.36 5364.74    9.99 5454.97   23.36
  5457.6   23.73 5580.87   21.16 6098.27   23.94 6141.69   21.07 6712.59   24.71
 6834.79   21.33 7089.64   23.48 7131.44   21.09 7221.26   23.59 8303.52   23.73
#Mann= 4 ,-1 , 0
 -344.76     .07       0 3028.07     .15       0 4545.03    .032       0
  5457.6     .15       0
#XS Ineff= 4 ,-1
 2040.61 3661.16   23.14 3756.96 4259.89   22.35 4363.67  4491.4   21.44
 5458.62 8303.52   23.75
Permanent Ineff=
       F       F       F       F
#Block Obstruct= 1 ,-1
 2873.16 3031.86   20.97
Bank Sta=4545.03,5454.97
XS Rating Curve= 0
Exp/Cntr=0.3,0.1

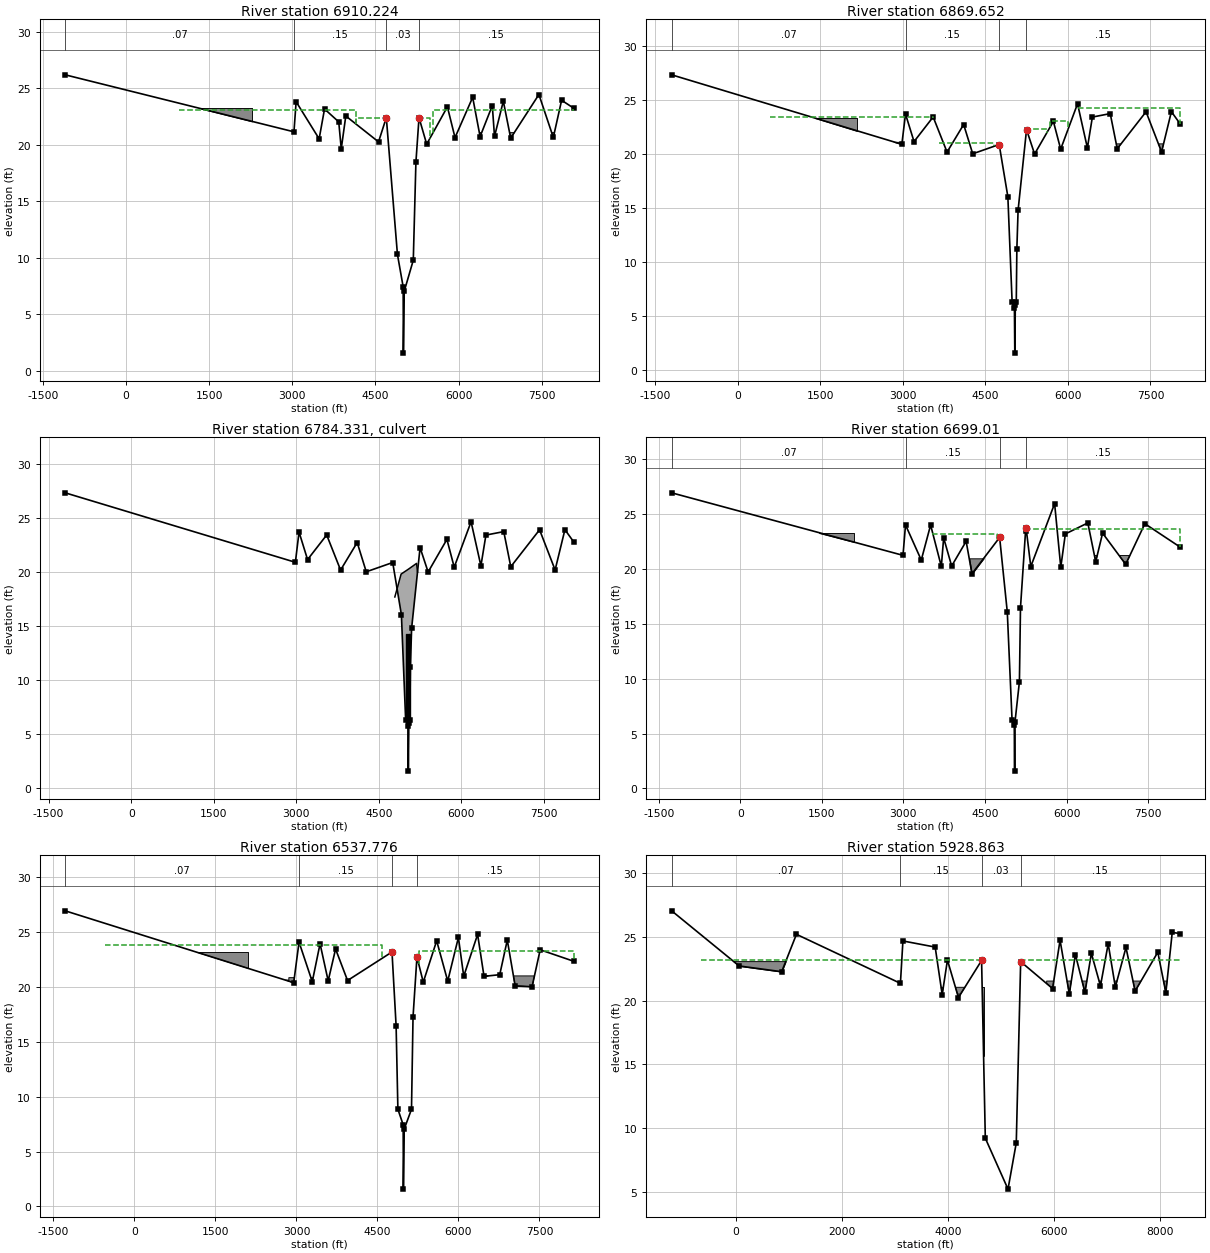
Type RM Length L Ch R = 1 ,6910.224,49.26,40.57,40.43
XS GIS Cut Line= 6
     3200692.295    13790551.169     3200441.916    13790401.204
       3195510.5    13787447.507       3195272.7    13787341.744
     3194697.981    13787079.856     3193071.769    13785542.751
#Sta/Elev= 30
-1095.67   26.19 3030.69   21.15 3069.93   23.81 3484.98   20.53 3582.24   23.17
 3838.53   22.03 3883.87   19.65 3965.97   22.55  4556.4   20.26 4696.84   22.41
 4897.42   10.31 5000.73    7.44 5004.74    1.58 5020.08    7.05 5183.35     9.8
 5230.77   18.47 5286.59    22.4 5425.06   20.06  5798.5   23.36  5936.3   20.64
 6254.67    24.2 6388.58   20.73 6608.66   23.47 6648.49   20.74 6807.47   23.86
 6940.44   20.59 7449.54   24.45 7709.39   20.65 7858.88   23.94 8074.03   23.25
#Mann= 4 ,-1 , 0
-1095.67     .07       0 3030.69     .15       0 4696.84     .03       0
 5286.59     .15       0
#XS Ineff= 4 ,-1
  962.46    4157   23.04    4157 4698.13   22.38 5293.74 5479.64   22.41
 5535.84 8074.03    23.1
Permanent Ineff=
       F       F       F       F
#Block Obstruct= 3 ,-1
 1356.08 2274.02   23.26 1959.04 3215.02   21.07 6245.73 8798.63   21.08
Bank Sta=4696.84,5286.59
XS Rating Curve= 0
Exp/Cntr=0.5,0.3

Type RM Length L Ch R = 1 ,6869.652,143.01,170.64,215.16
XS GIS Cut Line= 6
     3200783.005    13790546.048     3200505.689    13790380.632
     3195528.229    13787411.614     3195289.121     13787305.27
     3194720.622    13787046.216     3193099.245    13785513.681
#Sta/Elev= 30
-1199.18   27.34 2982.91   20.91 3049.42   23.71 3204.42   21.16 3551.87   23.44
 3804.27   20.19    4106   22.74 4270.81   20.03  4751.4   20.89 4909.15   16.06
 4986.88    6.27 5028.24    5.76 5035.26    1.58 5044.77    6.04 5061.84    6.27
 5072.74   11.25  5094.9    14.8  5248.6   22.27 5394.76   20.01 5736.25   23.03
 5868.85   20.46 6175.21   24.66 6353.94   20.58 6444.95   23.43  6769.2   23.75
 6896.67    20.5 7419.91   23.92 7702.17    20.2 7880.41   23.93  8036.9   22.82
#Mann= 4 ,-1 , 0
-1199.18     .07       0 3049.42     .15       0  4751.4     .03       0
 5238.38     .15       0
#XS Ineff= 5 ,-1
   580.2 3556.31   23.42 3663.25 4662.02   21.01 5256.32 5617.33   22.32
 5672.35    6000    23.1 6177.47  8036.9    24.3
Permanent Ineff=
       F       F       F       F       F
#Block Obstruct= 3 ,-1
 1315.64 2176.96   23.34 2259.39 3064.85   21.14 6095.56 8935.15   20.95
Bank Sta=4751.4,5248.6
XS Rating Curve= 0
Exp/Cntr=0.5,0.3

Type RM Length L Ch R = 2 ,6784.331,,,
Node Photo=G:\C2001-041_Harris_County_FEMA\1-Armand_Bayou\Horsepen_Bayou_Trib_4.51\Survey info\3113S02\311302P01 (7).JPG
BEGIN DESCRIPTION:
Almond Creek
END DESCRIPTION:
Bridge Culvert--1,0,-1,-1, 0
Deck Dist Width WeirC Skew NumUp NumDn MinLoCord MaxHiCord MaxSubmerge Is_Ogee
44.248,71,2.6,0, 5, 5, , , 0.95, 0, 0,0,,
    4790 4903.96  5035.8    5185    5203
    17.7   19.82   20.27   20.81      20
       0       0       0       0       0
    4799 4912.96  5044.8    5194    5212
    17.7   19.82   20.27   20.81      20
       0       0       0       0       0
BR Coef=-1 , 0 , 0 ,, 0 ,,,0.8,0,,0,
WSPro=,,,, 1 ,,,, 0 ,,,, 0 ,,,,-1 ,-1 ,-1 , 0 , 0 , 0 , 0 , 0
Multiple Barrel Culv=2,8,12,71,0.012,0.5,1,10,1,6.238,6.238, 5,Culvert #1  , 0 ,44.248
 4997.84 4997.84 5012.44 5012.44 5027.04 5027.04 5041.64 5041.64 5056.24 5056.24
Culvert Bottom n=0.012
BC Design=,, 0 ,, 0 ,,,,,,
BC HTab HWMax=27.34

Type RM Length L Ch R = 1 ,6699.01 ,163.44,161.23,160.96
XS GIS Cut Line= 6
     3200838.924    13790542.892     3200552.817    13790365.429
     3195631.259    13787312.744      3195320.31    13787079.532
      3193443.51    13785669.156     3193057.593    13785379.147
#Sta/Elev= 30
-1261.39   26.91 2992.53   21.22 3038.32   23.99 3328.12   20.79 3500.04   23.98
    3697   20.21 3739.75   22.81 3886.99   20.25  4153.4    22.5 4260.08   19.54
 4769.14   22.85    4910   16.06  4997.3    6.27 5038.24    5.76 5045.26    1.58
 5050.56    6.01    5133    9.72 5152.58   16.46 5246.54   23.48 5255.29   23.72
 5342.01    20.2 5780.22   25.93 5893.53   20.14 5977.58   23.17 6390.85   24.17
  6535.9   20.64 6662.28   23.24 7087.18    20.4 7439.67    24.1  8085.8   21.98
#Mann= 4 ,-1 , 0
-1261.39     .07       0 3038.32     .15       0 4769.14     .03       0
 5246.54     .15       0
#XS Ineff= 3 ,-1
   552.9 3501.71    23.8 3529.01 4716.72   23.16 5249.15  8085.8   23.61
Permanent Ineff=
       F       F       F
#Block Obstruct= 5 ,-1
   921.5 2095.56   23.29 3351.54 4539.25   20.44 4170.65 4716.72   20.95
  5290.1 7569.97   20.44 6068.26 8593.86    21.2
Bank Sta=4769.14,5255.29
XS Rating Curve= 0
Exp/Cntr=0.5,0.3

Type RM Length L Ch R = 1 ,6537.776,564.16,608.91,576.49
XS GIS Cut Line= 6
     3200850.132    13790542.259     3200571.305    13790359.465
     3195717.336    13787177.301      3195416.37    13786951.577
     3193539.631    13785541.247     3193098.332    13785209.619
#Sta/Elev= 30
-1282.68   26.94 2948.54   20.39 3047.43   24.09 3292.42   20.48 3436.64   23.94
 3586.99   20.56    3724   23.46 3945.83   20.59    4769   23.19    4845   16.46
    4878    8.86 4975.73    7.44 4979.74    1.58 4995.08    7.05    5130    8.86
 5158.35   17.27    5231   22.74 5347.85   20.44 5596.11   24.21  5800.7   20.54
 5998.48   24.51 6097.27   20.98 6354.38   24.79 6472.95   20.97 6764.05   21.12
 6903.94   24.28  7049.5    20.1 7362.63   20.02 7513.18   23.39  8130.6   22.35
#Mann= 4 ,-1 , 0
-1282.68     .07       0 3047.43     .15       0    4769     .03       0
    5231     .15       0
#XS Ineff= 2 ,-1
 -539.25  4580.2    23.8  5262.8  8130.6   23.29
Permanent Ineff=
       F       F
#Block Obstruct= 5 ,-1
 1126.28 2095.56   23.16 1931.74 4566.55   20.63 2858.58 3663.71   20.85
  5262.8 8416.38   20.57 6045.15 9212.42   21.01
Bank Sta=4769,5231
XS Rating Curve= 0
Exp/Cntr=0.3,0.1

Type RM Length L Ch R = 1 ,5928.863,76.99,75.38,77.05
XS GIS Cut Line= 5
     3200883.559    13790540.372     3200628.355    13790341.062
     3197774.586    13788112.327     3193921.039    13785102.784
     3193329.369    13784640.702
#Sta/Elev= 30
-1205.79   27.03   67.09   22.71  868.37   22.26 1146.71   25.19 3107.46   21.35
 3154.54   24.67 3762.87   24.19 3895.12   20.47 3994.05   23.17 4201.89   20.24
 4637.91   23.14 4708.15    9.22 5136.03    5.23 5291.79    8.85 5374.79   23.05
 5976.75   20.94 6117.46   24.73 6291.82   20.52 6406.57    23.6 6586.96   20.64
 6707.86    23.7 6879.58   21.15 7025.26   24.45 7159.97   21.06 7360.48   24.16
 7532.74   20.74 7960.83   23.79 8112.57   20.62 8232.83   25.34  8379.2   25.25
#Mann= 4 ,-1 , 0
-1205.79     .07       0 3107.46     .15       0 4637.91     .03       0
 5374.79     .15       0
#XS Ineff= 2 ,-1
 -662.12 4621.16    23.2 5412.97  8379.2   23.14
Permanent Ineff=
       F       F
#Block Obstruct= 5 ,-1
-1836.18 4675.77   21.04-1058.02 2163.82   23.09 2668.94 4443.69   20.51
 5453.92 8170.65   20.98 5865.05 8569.81   21.53
Bank Sta=4637.91,5374.79
XS Rating Curve= 0
Exp/Cntr=0.5,0.3

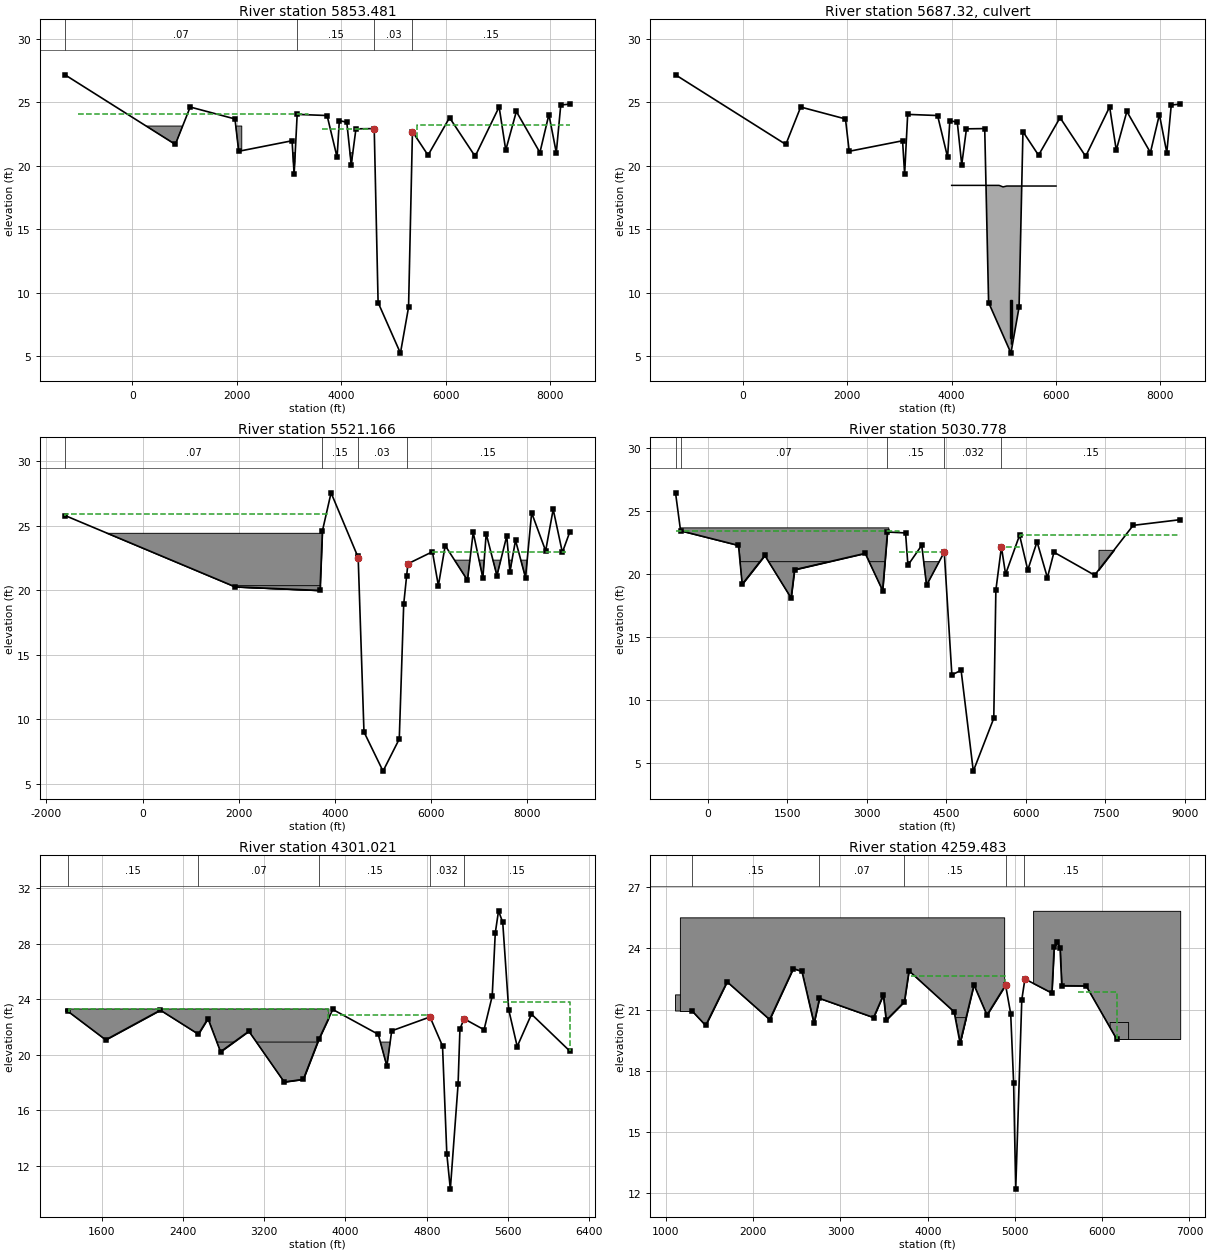
Type RM Length L Ch R = 1 ,5853.481,320.54,332.32,394.51
XS GIS Cut Line= 6
     3200992.283    13790534.234     3200710.987    13790314.407
     3197807.902    13788045.695     3196309.154    13786874.449
     3195754.728    13786438.311      3193372.69    13784579.912
#Sta/Elev= 30
-1290.98   27.18  822.73   21.69 1107.42   24.64  1965.5    23.7 2037.04   21.15
 3059.54   21.98 3099.04   19.34  3157.3   24.06 3730.49   23.97 3922.44   20.68
 3965.24   23.57 4108.14   23.44 4193.21   20.09 4283.74   22.92 4633.76   22.94
 4708.15    9.22 5136.03    5.23 5291.79    8.85 5366.24    22.7 5664.94   20.84
 6077.41    23.8 6567.79   20.75 7027.34   24.65  7154.3   21.24 7357.21   24.29
 7808.69   21.05 7981.02   24.05 8122.66   21.04 8208.21    24.8 8379.19   24.87
#Mann= 4 ,-1 , 0
-1290.98     .07       0  3157.3     .15       0 4633.76     .03       0
 5366.24     .15       0
#XS Ineff= 3 ,-1
-1044.37 3365.19   24.09 3640.91 4629.44   22.94 5444.58 8379.19   23.19
Permanent Ineff=
       F       F       F
#Block Obstruct= 4 ,-1
-1740.61  4552.9   21.03 -389.08 2095.56   23.14 2668.94 4443.69    20.4
 5452.97 9142.53   20.99
Bank Sta=4633.76,5366.24
XS Rating Curve= 0
Exp/Cntr=0.5,0.3

Type RM Length L Ch R = 2 ,5687.32 ,,,
BEGIN DESCRIPTION:
PIPELINE Right of Way
END DESCRIPTION:
Bridge Culvert--1,0,-1,-1, 0
Deck Dist Width WeirC Skew NumUp NumDn MinLoCord MaxHiCord MaxSubmerge Is_Ogee
94,174,2.6,0, 5, 5, , , 0.95, 0, 0,0,,
    4000    4910    4985    5056    6000
   18.46   18.46   18.34   18.41   18.41
                                        
    4000    4910    4985    5056    6000
   18.46   18.46   18.34   18.41   18.41
                                        
Culvert=2,3,6,242,0.015,0.2,1,8,1,6.43,5125,6.43,4990,Culvert #1  , 0 ,60
Culvert Bottom n=0.015
Culvert=2,3,6,242,0.015,0.2,1,8,1,5.93,5133,5.93,4998,Culvert #2  , 0 ,60
Culvert Bottom n=0.015
Culvert=2,3,6,242,0.015,0.2,1,8,1,5.93,5140,5.93,5005,Culvert #3  , 0 ,60
Culvert Bottom n=0.015
Culvert=2,3,6,242,0.015,0.2,1,8,1,6.43,5147,6.43,5012,Culvert #4  , 0 ,60
Culvert Bottom n=0.015
BC Design=,, 0 ,, 0 ,,,,,,
BC HTab HWMax=27.6

Type RM Length L Ch R = 1 ,5521.166,424.1,490.39,573.98
XS GIS Cut Line= 5
     3201240.257    13790520.236     3200911.701     13790249.66
     3197952.272    13787812.483     3194176.462    13784702.993
     3193137.744    13783847.578
#Sta/Elev= 30
-1614.62    25.8 1922.01   20.27 3689.15   19.99 3738.57    24.6 3918.97   27.56
 4473.32   22.63 4482.76   22.53 4603.25    9.02 4999.69    5.98 5337.35    8.47
 5429.75   18.93 5490.55   21.12 5517.25   22.06 6027.01   22.99 6150.66   20.36
 6292.61   23.47 6756.25   20.78 6875.07   24.49 7076.34   20.96 7145.19   24.39
 7368.88   21.14 7572.83   24.21 7639.29   21.44 7755.15   23.88 7963.53   20.98
 8090.66   26.01 8381.99   23.06 8538.85   26.28 8729.73   22.94 8881.83    24.5
#Mann= 4 ,-1 , 0
-1614.62     .07       0 3738.57     .15       0 4473.32     .03       0
 5490.55     .15       0
#XS Ineff= 3 ,-1
-1614.62 3870.31   25.89 5522.85  6027.3   22.05  6027.3 8812.29   22.99
Permanent Ineff=
       F       F       F
#Block Obstruct= 4 ,-1
-1481.23 3883.96   24.46 1344.71 4088.74    20.4 5535.84 5808.87    20.4
 6255.46 8515.52   22.34
Bank Sta=4482.76,5517.25
XS Rating Curve= 0
Exp/Cntr=0.5,0.3

Type RM Length L Ch R = 1 ,5030.778,311.47,729.76,749.33
XS GIS Cut Line= 6
     3200764.785     13789615.26     3198489.323    13787747.716
     3196817.779    13786375.826       3196142.3    13785685.873
     3194618.536    13784523.244     3193403.949    13783596.516
#Sta/Elev= 30
 -606.32   26.41 -511.16    23.4  580.22   22.24  651.34   19.16 1077.44   21.44
 1573.25   18.07 1639.06   20.31 2970.24   21.61 3299.25   18.66 3390.45    23.3
 3731.47   23.23 3775.73   20.67  4036.5   22.25 4127.39   19.08 4460.98   21.71
 4604.66   11.97 4778.63   12.34 5008.75    4.34 5394.66    8.53 5434.32    18.7
 5539.02   22.11 5617.34   19.96 5881.46   23.05  6035.8   20.29 6210.67   22.53
 6405.87   19.68 6529.86    21.7 7296.16   19.88 8022.95   23.83 8909.81   24.28
#Mann= 5 ,-1 , 0
 -606.32     .15       0 -511.16     .07       0 3390.45     .15       0
 4460.98    .032       0 5539.02     .15       0
#XS Ineff= 4 ,-1
 -606.32 3610.92   23.42 3610.92 4457.71   21.72 5532.84 5890.79   22.12
 5890.79 8909.81    23.1
Permanent Ineff=
       F       F       F       F
#Block Obstruct= 3 ,-1
 -825.94 3406.14   23.67  -34.13 4443.69   20.95 7369.13 8107.56   21.89
Bank Sta=4460.98,5539.02
XS Rating Curve= 0
Exp/Cntr=0.3,0.1

Type RM Length L Ch R = 1 ,4301.021,41.37,41.54,56.23
XS GIS Cut Line= 6
     3200205.698     13788157.52     3197485.739    13786557.544
     3197204.061    13786343.468     3196719.942     13785780.71
     3196539.608    13785498.938     3196404.987    13785173.605
#Sta/Elev= 30
 1267.16   23.14 1639.36   21.08 2177.74   23.22 2551.67   21.49 2646.17   22.61
 2770.21   20.22 3048.83    21.7 3397.29   18.04 3585.15   18.23 3737.38   21.11
 3875.05   23.27  4322.7   21.48  4407.8   19.19 4455.35   21.73 4832.26   22.73
 4955.58   20.64 4998.01   12.86 5032.53   10.32 5108.75   17.87 5127.09   21.86
 5167.74    22.6 5364.39   21.81 5444.79   24.23 5474.97   28.78 5507.14   30.38
 5548.53   29.54 5607.08   23.26    5691    20.6 5831.59   22.93  6207.6   20.28
#Mann= 5 ,-1 , 0
 1267.16     .15       0 2551.67     .07       0 3737.38     .15       0
 4832.26    .032       0 5167.74     .15       0
#XS Ineff= 3 ,-1
 1279.86 3832.76   23.29 3866.89 4822.53   22.87  5552.9  6207.6   23.82
Permanent Ineff=
       F       F       F
#Block Obstruct= 2 ,-1
 1238.91 3832.76   23.34 2672.35 4488.05   20.92
Bank Sta=4832.26,5167.74
XS Rating Curve= 0
Exp/Cntr=0.5,0.3

Type RM Length L Ch R = 1 ,4259.483,231.33,227.3,549.48
XS GIS Cut Line= 6
     3200182.714    13788097.593     3197508.059    13786524.266
     3197230.426    13786313.265     3196752.897    13785757.998
     3196575.211    13785480.365     3196441.948    13785158.311
#Sta/Elev= 30
 1300.11   20.93  1454.6   20.22 1700.62   22.36 2188.39   20.51 2459.12   23.01
 2557.67   22.87 2696.76   20.32 2759.41   21.55 3379.24   20.61 3491.79   21.72
  3523.8   20.48 3732.27   21.38  3785.4    22.9 4302.63   20.89 4370.37   19.36
 4529.74   22.21  4678.8   20.73  4892.5    22.2    4951    20.8 4984.62   17.41
 5008.66    12.2  5078.2   21.48 5114.15    22.5 5423.05   21.81 5449.56   24.06
 5486.28   24.29 5516.83   24.02 5536.37   22.17  5815.9   22.16 6164.44   19.56
#Mann= 5 ,-1 , 0
 1300.11     .15       0 2759.41     .07       0 3732.27     .15       0
  4892.5    .032       0  5107.5     .15       0
#XS Ineff= 2 ,-1
 3805.46 4883.96   22.63 5723.55 6164.44   21.86
Permanent Ineff=
       F       F
#Block Obstruct= 5 ,-1
 1109.21 3832.76   21.72 1159.29 4876.11   25.52 4242.32 4542.66   20.63
 5207.96 6893.81   25.84 6085.32 6296.93   20.39
Bank Sta=4892.5,5114.15
XS Rating Curve= 0
Exp/Cntr=0.5,0.3

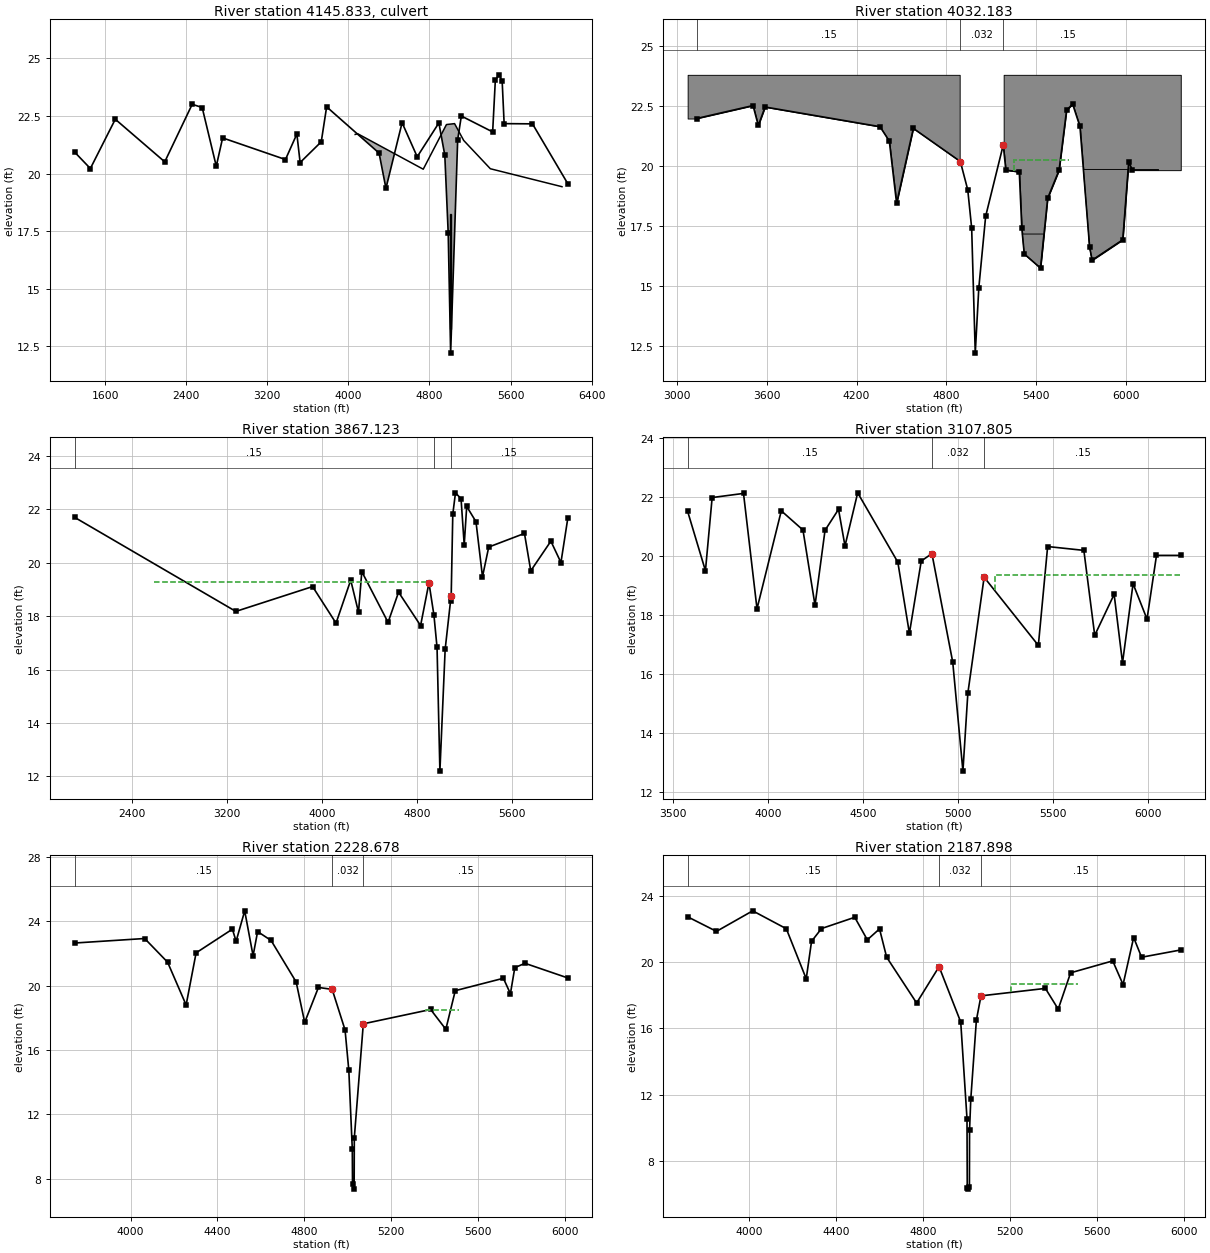
Type RM Length L Ch R = 2 ,4145.833,,,
Node Photo=G:\C2001-041_Harris_County_FEMA\1-Armand_Bayou\Horsepen_Bayou_Trib_4.51\Survey info\3113S04\311304P04.JPG
BEGIN DESCRIPTION:
Clear Lake Boulevard
END DESCRIPTION:
Bridge Culvert--1,0,-1,-1, 0
Deck Dist Width WeirC Skew NumUp NumDn MinLoCord MaxHiCord MaxSubmerge Is_Ogee
6.42,148.4,2.6,0, 8, 8, , , 0.95, 0, 0,0,,
    4067    4092 4738.34 4967.34 5047.34 5137.34 5400.34    6107
    21.7   21.73   20.19   22.13   22.17   21.44   20.21   19.43
       0       0       0       0       0       0       0       0
    4053    4078 4724.34 4953.34 5033.34 5123.34 5386.34    6093
    21.7   21.73   20.19   22.13   22.17   21.44   20.21   19.43
       0       0       0       0       0       0       0       0
BR Coef=-1 , 0 , 0 ,, 0 ,,,0.8,0,,0,
WSPro=,,,, 1 ,,,, 0 ,,,, 0 ,,,,-1 ,-1 ,-1 , 0 , 0 , 0 , 0 , 0
Culvert=2,5,5,148.4,0.012,0.5,1,8,1,13.2545,5009,13.2545,4993.37,Culvert #1  , 0 ,6.42
Culvert Bottom n=0.012
BC Design=,, 0 ,, 0 ,,,,,,
BC HTab HWMax=24.29

Type RM Length L Ch R = 1 ,4032.183,171.93,165.06,165.23
XS GIS Cut Line= 5
     3198807.381    13787079.532     3197541.375     13786324.37
     3197274.859    13786078.228     3197255.281    13786020.709
     3196797.318     13785113.89
#Sta/Elev= 30
 3129.31   21.97 3507.13   22.51 3542.36   21.68 3587.71   22.45  4356.3   21.63
 4418.72   21.03 4467.46   18.44 4579.28   21.56 4893.94   20.18 4943.42      19
 4969.62   17.41 4993.66    12.2  5017.4   14.92  5063.2    17.9 5180.92   20.87
 5198.32   19.82 5288.26   19.75 5304.97    17.4 5321.53   16.33 5430.31   15.74
 5478.06   18.65 5554.45   19.82 5604.67   22.32 5645.21   22.57 5693.99   21.64
 5758.77   16.61 5775.57   16.07 5980.51   16.92  6020.3   20.17 6042.88   19.82
#Mann= 3 , 0 , 0
 3129.31     .15       0 4893.94    .032       0 5180.92     .15       0
#XS Ineff= 2 ,-1
 4337.88 4576.79   21.27  5253.7    5624   20.23
Permanent Ineff=
       F       F
#Block Obstruct= 4 ,-1
 3069.69 4889.38   23.79 5183.63 6368.36   23.79 5261.66 6022.18   17.16
 5651.88 6213.31   19.85
Bank Sta=4893.94,5180.92
XS Rating Curve= 0
Exp/Cntr=0.5,0.3

Type RM Length L Ch R = 1 ,3867.123,751.87,759.32,727.27
XS GIS Cut Line= 6
 3200031.919047313787623.6565689     3198889.346    13786942.121
     3197637.671    13786195.507     3197435.048    13786041.535
     3197403.143    13785958.565     3196940.138    13785041.762
#Sta/Elev= 30
    1914    21.7 3272.94   18.18 3920.11   19.11 4117.74   17.74 4241.62   19.35
 4307.35   18.15 4335.04   19.67 4556.51   17.77 4645.14    18.9 4830.78   17.65
 4901.41   19.25 4943.42   18.04 4969.62   16.83 4993.66    12.2    5038   16.76
 5083.24   18.56 5088.94   18.76 5102.36   21.82 5125.01   22.62 5171.99    22.4
 5198.73   20.67 5219.68   22.11 5297.81   21.54 5352.83   19.48 5405.46   20.59
 5706.78    21.1 5759.95    19.7 5929.47   20.81 6014.35   20.01  6072.3   21.67
#Mann= 3 ,-1 , 0
    1914     .15       0 4943.42    .032       0 5083.24     .15       0
#XS Ineff= 1 ,-1
 2583.62 4904.44   19.27
Permanent Ineff=
       F
Bank Sta=4901.41,5088.94
XS Rating Curve= 0
Exp/Cntr=0.3,0.1

Type RM Length L Ch R = 1 ,3107.805,874.52,879.13,649.14
XS GIS Cut Line= 4
     3199151.646    13786646.424     3198127.548    13785773.154
     3198012.456    13785625.064     3197372.917    13784777.821
#Sta/Elev= 30
  3577.2   21.51 3670.84    19.5 3706.12   21.98 3871.18   22.12 3942.16   18.21
    4070   21.53 4184.02   20.88 4247.45   18.33 4300.13   20.87 4371.17   21.58
 4405.15   20.34 4471.97   22.14 4683.28   19.79 4744.13   17.38 4806.53   19.83
 4862.58   20.08 4972.28    16.4  5025.8   12.71  5051.7   15.35 5137.42   19.28
 5422.73   16.97 5471.61   20.32 5662.19   20.19 5719.38   17.31 5821.55    18.7
 5865.67   16.38 5921.13   19.06 5994.55   17.86 6044.44   20.02 6172.15   20.02
#Mann= 3 , 0 , 0
  3577.2     .15       0 4862.58    .032       0 5137.42     .15       0
#XS Ineff= 2 ,-1
 3626.28 4858.36   20.03 5192.83 6172.15   19.34
Permanent Ineff=
       F       F
Bank Sta=4862.58,5137.42
XS Rating Curve= 0
Exp/Cntr=0.3,0.1

Type RM Length L Ch R = 1 ,2228.678,41.67,40.78,40.55
XS GIS Cut Line= 3
     3199807.587    13785552.311     3198726.469    13785261.834
     3197637.396    13784886.862
#Sta/Elev= 30
 3742.37   22.65 4064.68   22.93 4170.21   21.46 4255.61    18.8 4301.61   22.04
 4468.68   23.51 4485.89   22.76  4525.4   24.65 4563.98   21.86 4584.89   23.36
 4646.91   22.81 4762.44   20.23 4801.73   17.72 4865.02   19.89 4928.27   19.77
 4987.65   17.25    5005   14.74 5020.98    9.85 5022.01    7.67 5029.51    7.36
 5030.27   10.55 5071.73   17.63 5381.91   18.52 5451.84   17.29 5495.31   19.69
 5716.96   20.46  5749.3    19.5 5769.48   21.12 5816.38   21.39 6013.65   20.48
#Mann= 3 , 0 , 0
 3742.37     .15       0 4928.27    .032       0 5071.73     .15       0
#XS Ineff= 2 ,-1
 4732.08 4902.73    19.8 5360.07 5513.65   18.49
Permanent Ineff=
       F       F
Bank Sta=4928.27,5071.73
XS Rating Curve= 0
Exp/Cntr=0.5,0.3

Type RM Length L Ch R = 1 ,2187.898,182.62,149.32,127.04
XS GIS Cut Line= 3
     3199817.966    13785513.681     3198738.183    13785223.563
     3197650.418    13784849.041
#Sta/Elev= 30
 3717.74   22.73 3850.33   21.85 4016.99   23.09 4171.65   22.01 4263.23   18.99
 4287.73   21.25 4333.44   22.02 4486.43    22.7 4544.28   21.34  4600.4      22
 4633.26   20.29 4771.07   17.53  4874.4   19.72 4974.03   16.38 5002.86   10.55
 5004.03    6.39 5008.87     6.3 5014.02    6.43 5014.61    9.86 5020.25   11.72
    5046   16.49 5067.19   17.96  5363.5   18.41 5422.49   17.16 5479.45   19.35
 5673.25   20.07 5720.82   18.64 5769.48   21.48 5806.09   20.29 5986.25   20.73
#Mann= 3 , 0 , 0
 3717.74     .15       0  4874.4    .032       0 5067.19     .15       0
#XS Ineff= 2 ,-1
 4606.37 4873.72   19.63 5203.64 5513.65   18.65
Permanent Ineff=
       F       F
Bank Sta=4874.4,5067.19
XS Rating Curve= 0
Exp/Cntr=0.5,0.3