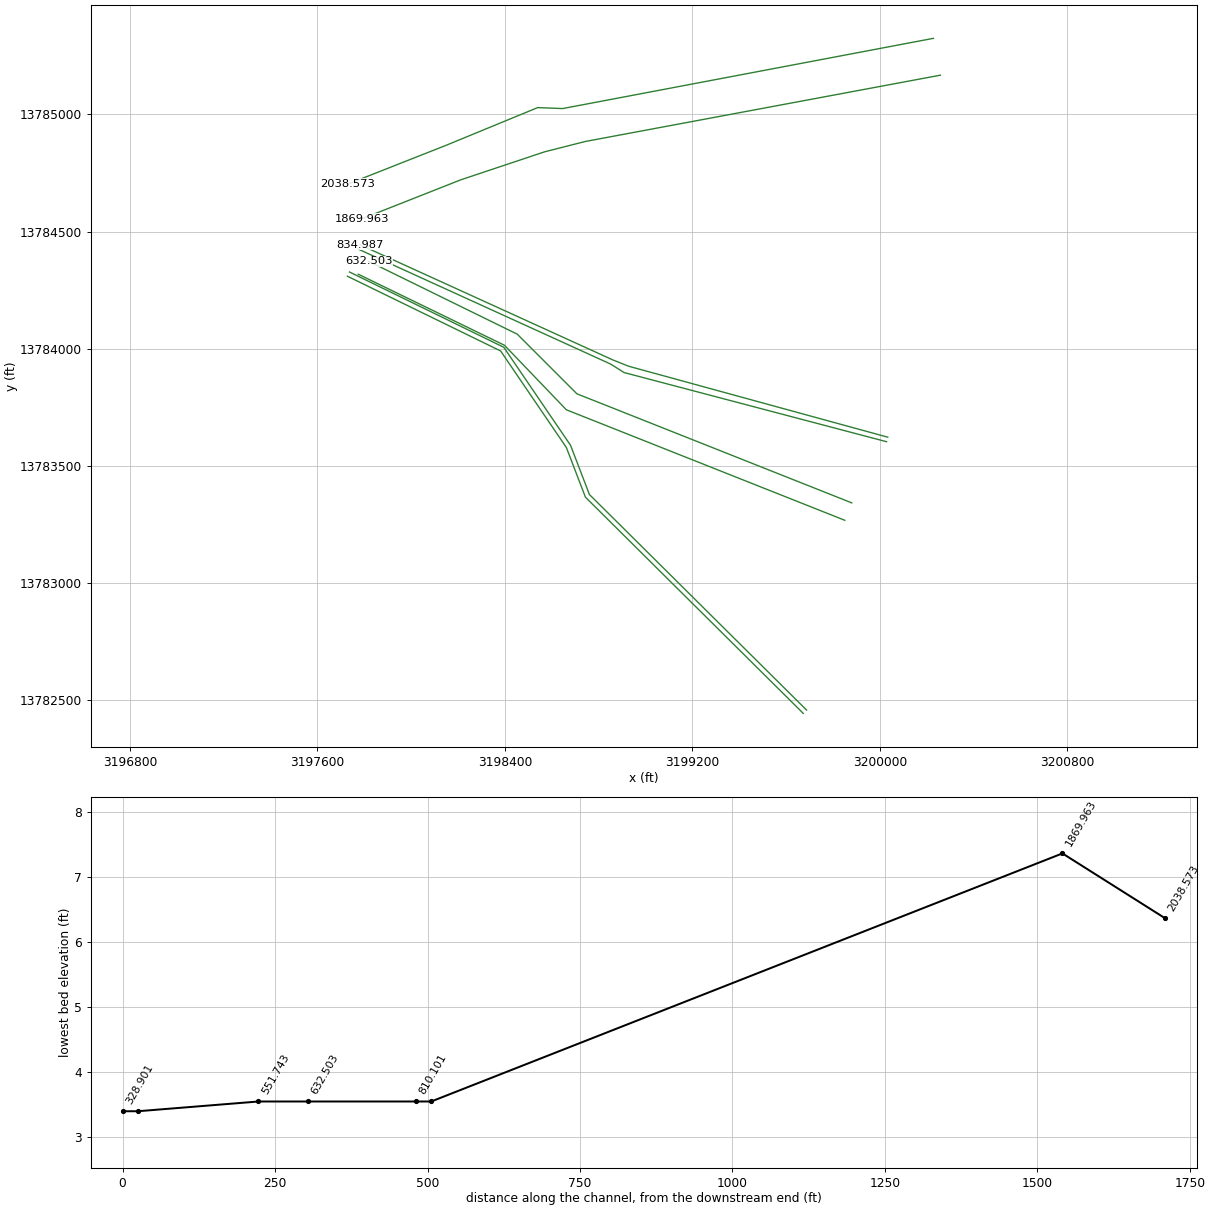
HEC-RAS study B104_04_00.prj: B104-04-00

--- B104_04_00.g02 (geometry) --- (continued)

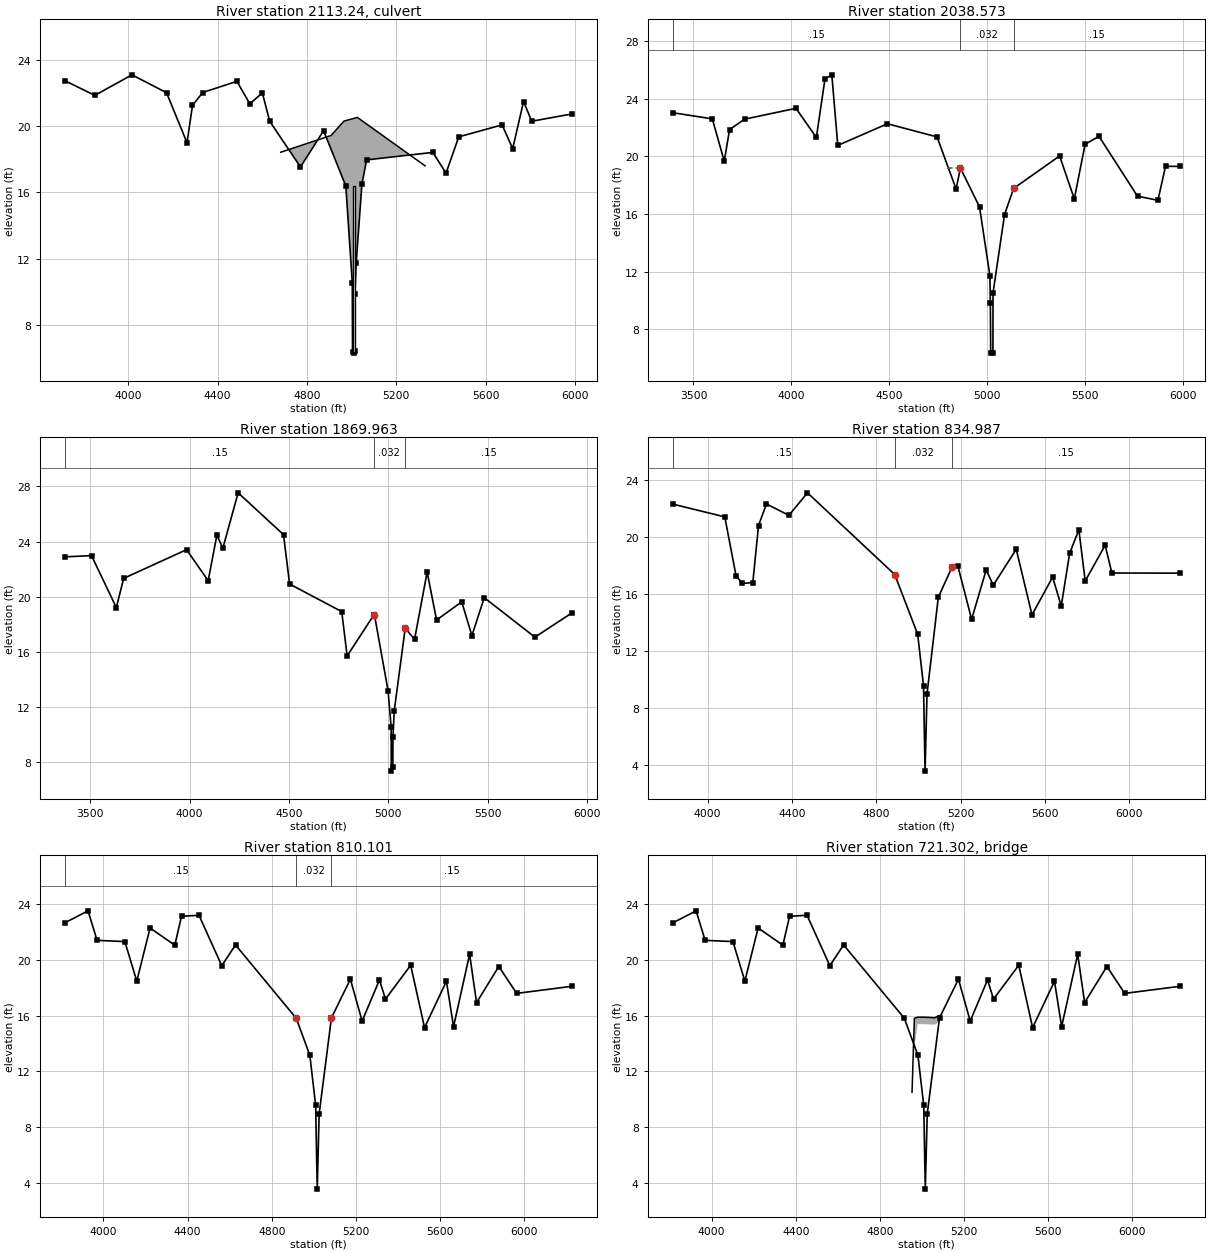
Type RM Length L Ch R = 2 ,2113.24 ,,,
Node Photo=G:\C2001-041_Harris_County_FEMA\1-Armand_Bayou\Horsepen_Bayou_Trib_4.51\Survey info\3113S05\311305P08.JPG
BEGIN DESCRIPTION:
Oak Links @ Almond Creek
END DESCRIPTION:
Bridge Culvert--1,0,-1,-1, 0
Deck Dist Width WeirC Skew NumUp NumDn MinLoCord MaxHiCord MaxSubmerge Is_Ogee
23.56,51.17,2.6,0, 5, 5, , , 0.95, 0, 0,0,,
 4682.75 4907.75 4965.75 5025.75 5328.75
   18.42   19.43    20.3   20.52    17.6
       0       0       0       0       0
 4682.75 4907.75 4965.75 5025.75 5328.75
   18.42   19.43    20.3   20.52    17.8
       0       0       0       0       0
BR Coef=-1 , 0 , 0 ,, 0 ,,,0.8,0,,0,
WSPro=,,,, 1 ,,,, 0 ,,,, 0 ,,,,-1 ,-1 ,-1 , 0 , 0 , 0 , 0 , 0
Culvert=2,10,10,51.17,0.012,0.4,1,8,1,6.3851,5009,6.3851,5025,Culvert #1  , 0 ,23.56
Culvert Bottom n=0.012
BC Design=,, 0 ,, 0 ,,,,,,
BC HTab HWMax=22.78

Type RM Length L Ch R = 1 ,2038.573,157.24,168.61,182.45
XS GIS Cut Line= 5
     3200228.863    13785324.891     3198646.643    13785025.223
     3198540.071    13785029.303     3198152.167    13784869.573
     3197730.165    13784702.993
#Sta/Elev= 30
 3396.38   23.01 3596.23   22.59  3657.3   19.65 3684.24   21.85 3761.78   22.57
  4023.7   23.32 4128.02    21.3  4171.9   25.36  4206.9   25.64 4237.43   20.75
 4490.93   22.25 4744.65   21.34 4841.86   17.73 4864.12   19.18 4961.67   16.49
 5014.75   11.72 5017.19     9.8 5018.81    6.36 5030.22    6.36 5030.77   10.53
 5089.59   15.96 5135.88   17.77 5371.04   20.02 5446.05   17.04  5501.2   20.83
 5572.16   21.38 5769.04   17.23 5873.38   16.95 5912.24    19.3 5986.57    19.3
#Mann= 3 , 0 , 0
 3396.38     .15       0 4864.12    .032       0 5135.88     .15       0
#XS Ineff= 2 ,-1
  5368.6  5525.6   19.93 4795.22 4866.89   19.19
Permanent Ineff=
       F       F
Bank Sta=4864.12,5135.88
XS Rating Curve= 0
Exp/Cntr=0.5,0.3

Type RM Length L Ch R = 1 ,1869.963,1088.96,1034.98,800.76
XS GIS Cut Line= 5
     3200258.637    13785167.686     3198743.691    13784884.841
     3198570.199    13784840.779     3198212.005    13784721.178
     3197788.912    13784554.168
#Sta/Elev= 30
  3372.9   22.89 3505.76   22.98  3630.8   19.21 3667.51   21.33 3984.42   23.41
 4093.31   21.16 4137.02   24.46 4167.23   23.52 4244.12   27.53 4472.72    24.5
 4503.24   20.92 4765.87   18.92 4793.16   15.71 4926.75   18.66 4930.73   18.68
 4999.17   13.19 5014.73   10.55 5015.49    7.36 5022.99    7.67 5024.02    9.85
 5030.25   11.72 5085.44   17.71 5132.77   16.91 5196.02   21.79 5243.47   18.31
 5370.16   19.63 5421.47   17.18 5483.62   19.93  5738.9   17.07 5925.52   18.83
#Mann= 3 ,-1 , 0
  3372.9     .15       0 4926.75    .032       0 5085.44     .15       0
#XS Ineff= 1 ,-1
 4655.29 4924.91   18.55
Permanent Ineff=
       F
Bank Sta=4930.73,5085.44
XS Rating Curve= 0
Exp/Cntr=0.3,0.1

Type RM Length L Ch R = 1 ,834.987 ,29.67,24.89,22.58
XS GIS Cut Line= 4
     3200034.063    13783622.906       3198927.7    13783925.815
     3198860.901    13783952.539     3197782.877     13784443.56
#Sta/Elev= 30
  3836.7   22.28 4081.31   21.39 4134.73   17.25 4164.91   16.72 4214.21   16.78
 4241.24   20.78  4278.7    22.3 4385.39    21.5 4473.45   23.08 4887.35   17.34
 4996.02   13.15 5023.63    9.55 5031.01    3.54 5040.23    8.95 5093.94   15.75
 5159.06   17.87 5186.47   17.95 5251.76    14.2 5321.01   17.67 5354.45   16.59
 5463.31   19.12 5538.13   14.51 5635.82   17.16 5676.88   15.14 5716.62   18.83
 5760.39   20.49 5790.36   16.89 5884.96    19.4 5916.92   17.45 6240.31   17.44
#Mann= 3 , 0 , 0
  3836.7     .15       0 4887.35    .032       0 5159.06     .15       0
Bank Sta=4887.35,5159.06
XS Rating Curve= 0
Exp/Cntr=0.5,0.3

Type RM Length L Ch R = 1 ,810.101 ,183.35,177.6,167.06
XS GIS Cut Line= 4
     3200028.967    13783603.566     3198908.891    13783898.687
     3198851.384    13783934.897     3197774.586     13784425.36
#Sta/Elev= 30
 3817.67   22.68 3926.53   23.53 3969.42   21.41 4101.66   21.32 4158.21   18.48
 4221.39    22.3 4338.92   21.06 4370.91   23.14 4453.97   23.21 4562.16   19.59
 4627.62   21.08 4916.41   15.81 4981.02   13.15 5008.63    9.55 5016.01    3.54
 5025.23    8.95 5083.59   15.84 5173.65   18.62 5229.51   15.61 5311.92   18.57
 5340.37   17.19 5460.29   19.62  5526.2   15.14 5630.16   18.47 5664.13   15.21
 5740.47   20.41 5773.44   16.94  5879.3   19.53 5964.12    17.6 6227.17   18.11
#Mann= 3 , 0 , 0
 3817.67     .15       0 4916.41    .032       0 5083.59     .15       0
Bank Sta=4916.41,5083.59
XS Rating Curve= 0
Exp/Cntr=0.5,0.3

Type RM Length L Ch R = 3 ,721.302 ,,,
Node Photo=G:\C2001-041_Harris_County_FEMA\1-Armand_Bayou\Horsepen_Bayou_Trib_4.51\Survey info\3113S06\311306P01.JPG
BEGIN DESCRIPTION:
Golf Cart Bridge
END DESCRIPTION:
Bridge Culvert--1,0,-1,-1, 0
Deck Dist Width WeirC Skew NumUp NumDn MinLoCord MaxHiCord MaxSubmerge Is_Ogee
103.08,10,2.6,0, 6, 6, , , 0.95, 0, 0,0,,
    4953 4964.07 4979.83 5011.43    5061 5081.09
    10.5   15.81   15.89   15.89   15.85      16
       0       0   15.39   15.39   15.35       0
    5013 5024.07 5039.83 5071.43    5121 5141.09
    10.5   15.81   15.89   15.89   15.85      16
       0       0   15.39   15.39   15.35       0
BR Coef=-1 , 0 , 0 ,, 0 ,,,0.8,0,,1,
WSPro=,,,, 1 ,,,, 0 ,,,, 0 ,,,,-1 ,-1 ,-1 , 0 , 0 , 0 , 0 , 0
BC Design=,, 0 ,, 0 ,,,,,,
BC HTab HWMax=23.5

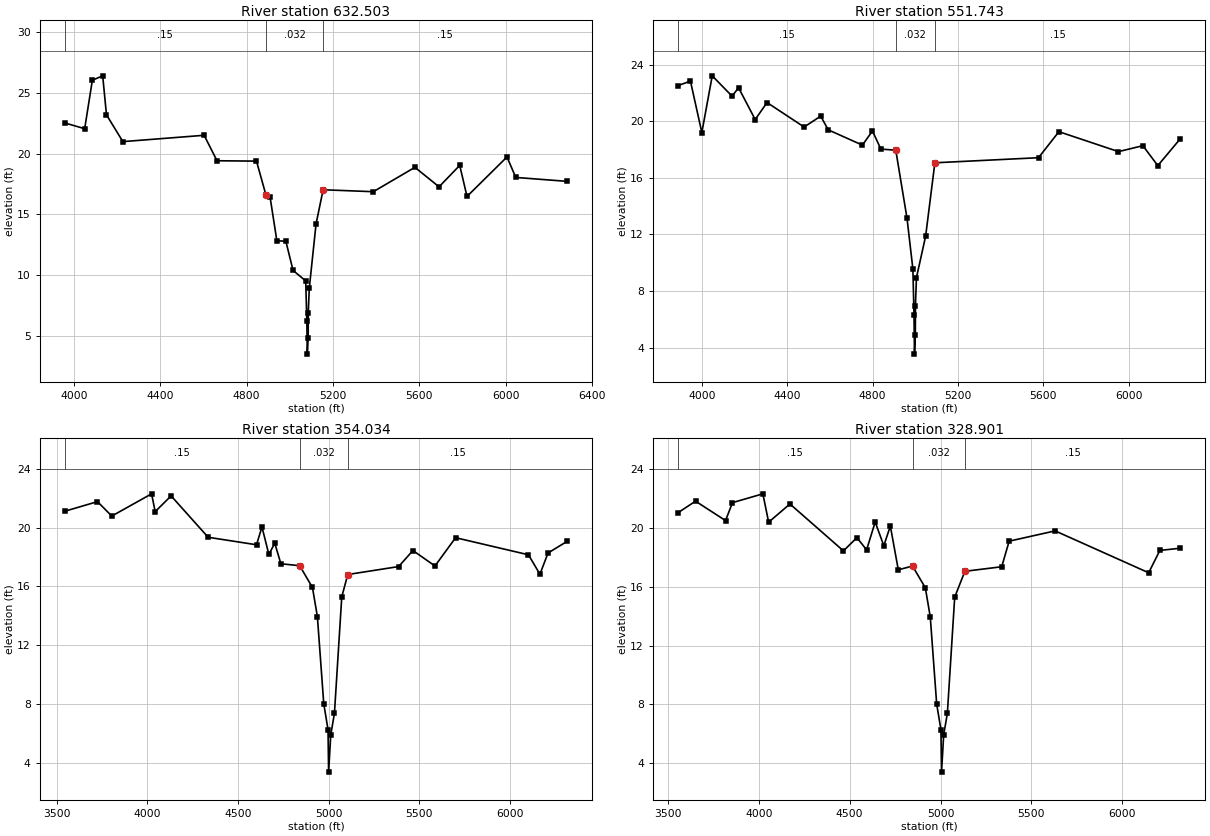
Type RM Length L Ch R = 1 ,632.503 ,80.76,80.76,101.22
XS GIS Cut Line= 4
     3199880.257    13783342.592     3198707.347    13783808.033
     3198452.906    13784062.474     3197819.907    13784372.767
#Sta/Elev= 30
 3957.94   22.51 4049.57   22.04 4085.17   26.02 4133.04   26.38 4150.56   23.18
 4226.58   20.98 4603.12    21.5 4662.68   19.41 4845.65   19.38 4888.89   16.63
 4908.76   16.41 4939.94   12.85 4981.74    12.8 5015.04   10.41 5073.63    9.55
 5078.86    6.28 5081.01    3.54 5085.16    4.87 5085.53    6.95 5090.23    8.95
 5121.55   14.22 5154.36   17.03  5386.9   16.87 5579.66   18.87 5691.48   17.27
 5787.23   19.03 5821.04   16.48 6006.17   19.72 6047.06   18.04 6284.62   17.72
#Mann= 3 , 0 , 0
 3957.94     .15       0 4888.89    .032       0 5154.36     .15       0
Bank Sta=4888.89,5154.36
XS Rating Curve= 0
Exp/Cntr=0.5,0.3

Type RM Length L Ch R = 1 ,551.743 ,338.91,197.71,72.01
XS GIS Cut Line= 4
      3199850.75    13783268.233      3198662.47    13783739.772
     3198398.213    13784015.199     3197774.335    13784318.351
#Sta/Elev= 30
 3888.28   22.53 3945.93   22.85 3999.36   19.21 4048.11   23.22 4141.19   21.78
 4171.39   22.38 4249.42   20.13    4305   21.33 4478.89    19.6 4556.46   20.37
 4591.85    19.4 4751.92   18.32 4799.07   19.32 4838.53   18.04 4908.42   17.96
 4961.02   13.15 4988.63    9.55 4993.86    6.28 4996.01    3.54 5000.16    4.87
 5000.53    6.95 5005.23    8.95 5048.32   11.88 5091.59   17.07  5577.4   17.43
 5672.96   19.27 5952.19   17.86 6066.63   18.28 6136.53   16.87 6242.03   18.77
#Mann= 3 ,-1 , 0
 3888.28     .15       0 4908.42    .032       0 5091.59     .15       0
Bank Sta=4908.42,5091.59
XS Rating Curve= 0
Exp/Cntr=0.3,0.1

Type RM Length L Ch R = 1 ,354.034 ,20.31,25.13,22.42
XS GIS Cut Line= 5
      3199687.45    13782458.479     3198760.973    13783378.054
     3198680.249    13783588.338     3198395.433    13784006.505
     3197736.955    13784327.714
#Sta/Elev= 30
 3546.27   21.11 3725.86   21.76 3804.85   20.78 4024.29   22.29 4044.06   21.08
 4131.98   22.15 4336.21   19.34 4602.92   18.83    4633   20.04 4671.03   18.17
 4703.51   18.94 4737.29   17.54 4840.91   17.41 4911.39   15.93  4938.6   13.95
 4973.77    8.03 4997.23    6.28 5000.52    3.39 5012.41    5.93 5032.61    7.38
 5073.01   15.29 5106.12   16.81 5386.59   17.35 5465.45   18.44 5587.04   17.39
 5700.76   19.31 6102.46   18.15  6165.8   16.83 6210.38   18.27 6315.47   19.06
#Mann= 3 , 0 , 0
 3546.27     .15       0 4840.91    .032       0 5106.12     .15       0
Bank Sta=4840.91,5106.12
XS Rating Curve= 0
Exp/Cntr=0.5,0.3

Type RM Length L Ch R = 1 ,328.901 ,112.87,161.92,181.81
XS GIS Cut Line= 5
     3199673.361    13782444.284     3198743.839    13783366.881
      3198662.41    13783579.001     3198381.892    13783990.857
     3197728.186    13784309.739
#Sta/Elev= 30
 3556.59   21.04 3652.27   21.82 3817.47    20.5 3855.42   21.72 4022.71   22.32
 4054.45   20.39 4171.55   21.63 4465.92   18.44 4540.03   19.34 4593.39   18.51
 4640.54    20.4  4688.1   18.79 4723.92   20.13 4767.76   17.15 4845.91   17.41
 4916.39   15.93  4943.6   13.95 4978.77    8.03 5002.23    6.28 5005.52    3.39
 5017.41    5.93 5037.61    7.38 5078.01   15.29 5133.99   17.05 5336.69   17.36
 5377.52    19.1 5630.33    19.8 6145.18   16.95 6206.61   18.47 6319.11   18.62
#Mann= 3 ,-1 , 0
 3556.59     .15       0 4845.91    .032       0 5133.99     .15       0
Bank Sta=4845.91,5133.99
XS Rating Curve= 0
Exp/Cntr=0.5,0.3