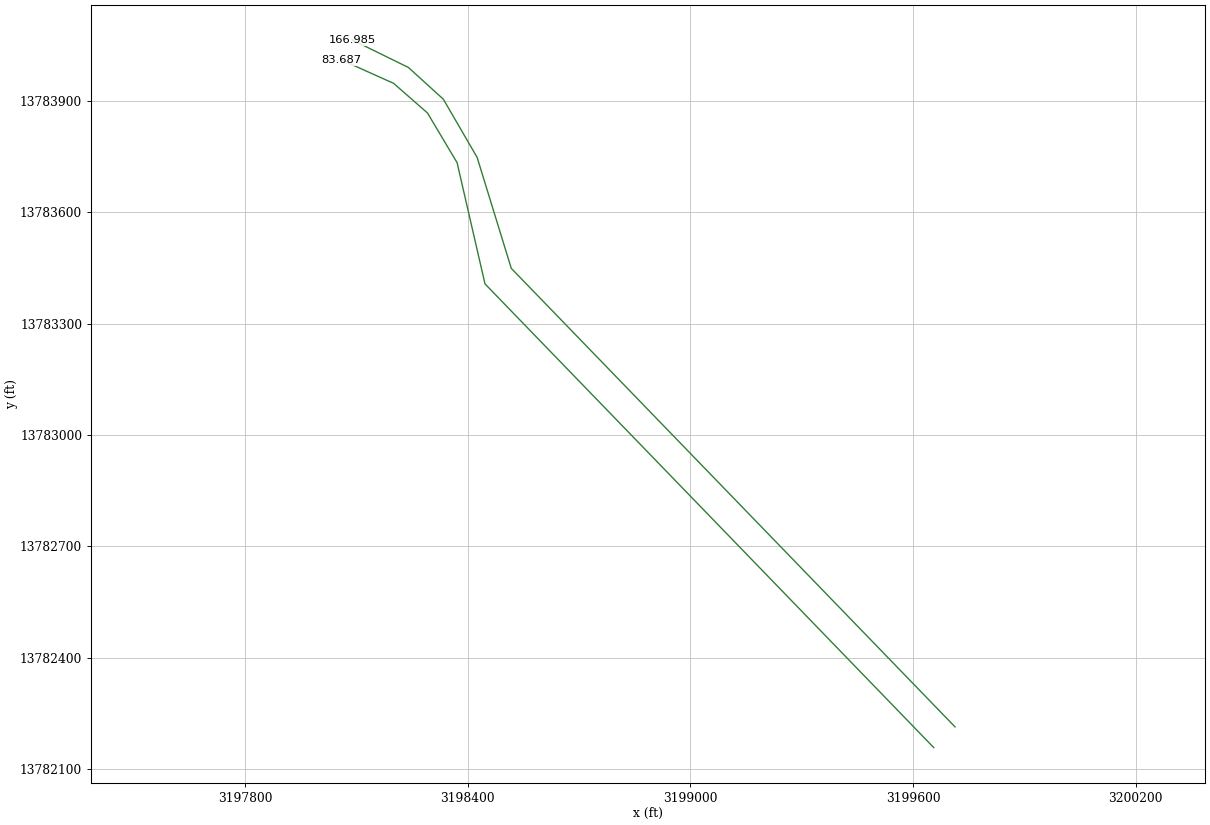
HEC-RAS study B104_04_00.prj: B104-04-00

--- B104_04_00.g02 (geometry) --- (continued)

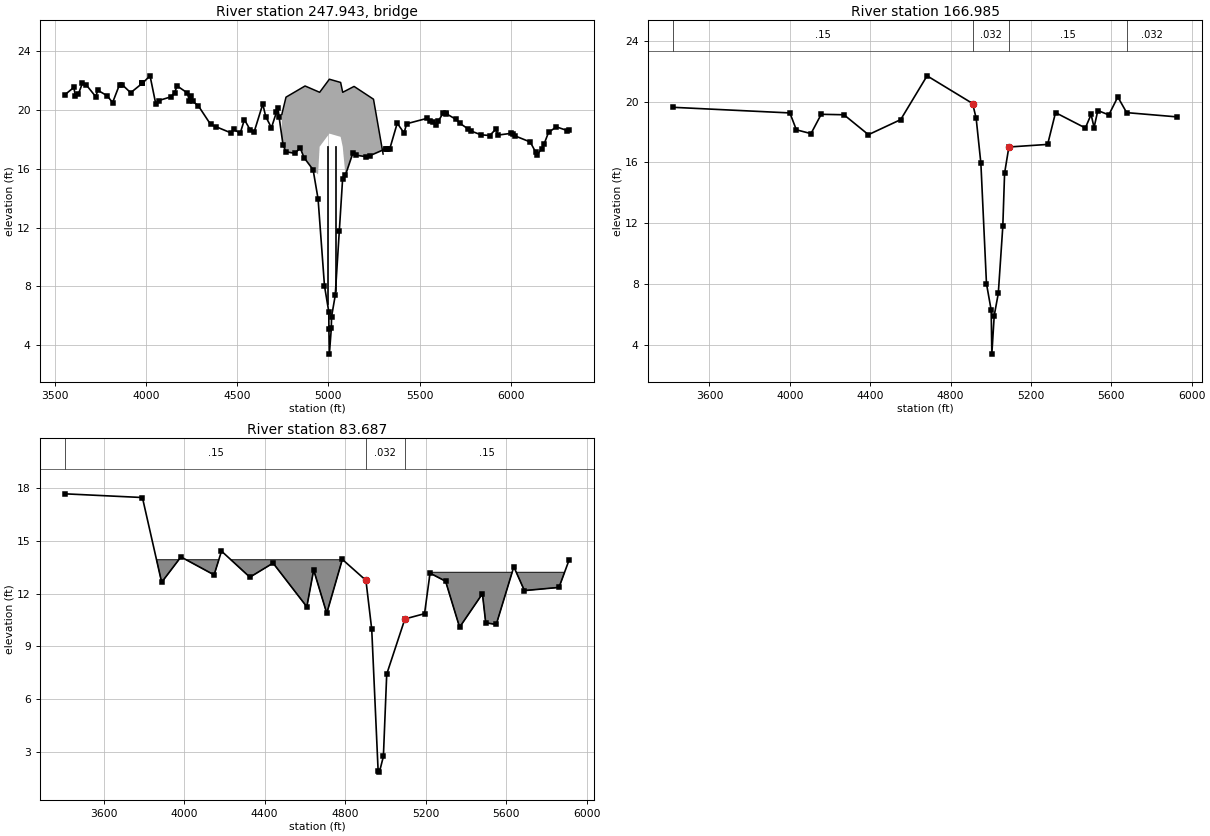
Type RM Length L Ch R = 3 ,247.943 ,,,
Node Photo=G:\C2001-041_Harris_County_FEMA\1-Armand_Bayou\Horsepen_Bayou_Trib_4.51\Survey info\311307S07\311307P01.JPG
BEGIN DESCRIPTION:
Bay Oaks Boulevard
END DESCRIPTION:
Bridge Culvert--1,0,-1,-1, 0
Deck Dist Width WeirC Skew NumUp NumDn MinLoCord MaxHiCord MaxSubmerge Is_Ogee
65.91,56.9,2.6,0, 10, 10, , , 0.95, 0, 0,0,,
    4745 4767.84 4872.21 4952.24 5005.43 5067.25 5078.61 5140.86 5247.38    5300
    19.7   20.87   21.63    21.2   22.09   21.87    21.2    21.6   20.73      17
       0       0       0    17.5   18.39   18.17    17.5       0       0       0
    4745 4767.84 4872.21 4952.24 5005.43 5067.25 5078.61 5140.86 5247.38    5300
    19.7   20.87   21.63    21.2   22.09   21.87    21.2    21.6   20.73      17
       0       0       0    17.5   18.39   18.17    17.5       0       0       0
Pier Skew, UpSta & Num, DnSta & Num=  ,4995.51, 4 ,4991.56, 4 , 3 , 3 , 0 ,,
     1.5     1.5     2.8     2.8
       0   14.98   14.98   17.58
     1.5     1.5     2.8     2.8
       0   14.98   14.98   17.58
Pier Skew, UpSta & Num, DnSta & Num=  ,5039.25, 4 ,5034.81, 4 , 3 , 3 , 0 ,,
     1.5     1.5     2.8     2.8
       0   14.96   14.97   17.57
     1.5     1.5     2.8     2.8
       0   14.96   14.97   17.57
BR Coef=-1 , 1 , 1 ,1.05, 0 ,,,0.8,0,2,0,
WSPro=,,,, 1 ,,,, 0 ,,,, 0 ,,,,-1 ,-1 ,-1 , 0 , 0 , 0 , 0 , 0
BR U #Sta/Elev= 97
 3556.59   21.04 3604.87   21.53 3613.45   20.98 3630.18   21.09 3652.27   21.82
 3673.33    21.7 3725.23    20.9 3736.25   21.34 3788.28   20.96 3817.47    20.5
 3855.42   21.72 3869.81   21.72 3916.56   21.17 3979.99   21.81 3980.18   21.81
  3980.6   21.81 4022.71   22.32 4054.45   20.39 4070.29   20.64 4137.36   20.89
 4156.86   21.18 4171.55   21.63 4226.64   21.16  4238.6   20.62 4249.15   20.95
 4256.73   20.58 4287.42   20.28 4354.31   19.02 4382.04   18.87 4465.92   18.44
  4481.2   18.67 4516.84   18.42 4540.03   19.34 4572.64   18.62 4593.39   18.51
 4640.54    20.4 4656.79   19.54  4688.1   18.79 4715.29   19.84 4723.92   20.13
 4730.23   19.49 4751.82   17.61 4767.76   17.15 4816.29   17.05 4845.91   17.41
 4866.39   16.76 4916.39   15.93  4943.6   13.95 4978.77    8.03 5002.23    6.28
 5002.92    5.12 5005.52    3.39  5016.2    5.15 5017.41    5.93 5037.61    7.38
 5060.11   11.79 5078.01   15.29 5093.61   15.57 5133.99   17.05  5152.4   16.92
  5206.2   16.82 5225.98   16.88 5313.16   17.35 5316.16   17.35 5326.55   17.36
 5336.69   17.36 5377.52    19.1 5414.65   18.43 5429.18   19.06 5538.22   19.42
  5558.7   19.24 5574.93    19.2 5591.77   18.96 5601.08   19.22 5630.33    19.8
 5642.17   19.78 5646.78   19.74 5697.96   19.37 5720.97   19.09 5765.39   18.71
 5779.43   18.58 5835.59   18.31 5884.69   18.26 5918.13    18.7 5930.23   18.29
 6002.64   18.41 6011.51   18.37 6021.92   18.24 6106.28   17.82 6135.72   17.14
 6145.18   16.95  6168.7   17.37 6183.14   17.71 6206.61   18.47 6249.43   18.85
 6308.74    18.6 6319.11   18.62
BR U #Mann= 3
 3556.59     .15 4845.91    .015 5133.99     .15
BR D #Sta/Elev= 119
 3418.41   19.62  3436.8   19.63  3455.4   19.48  3474.7   19.36 3547.62   19.95
 3560.01   19.93 3601.32   19.66 3612.13   19.59 3650.88   19.96 3651.88   19.94
 3714.23   19.11  3715.7    19.1 3717.59   19.11 3768.56   19.06 3819.44   19.35
  3821.6   19.37 3822.08   19.36 3846.89   19.04 3901.15      19 3906.47   18.89
  3907.6   18.89 3914.43   18.96 3991.33   18.87 4000.24   19.25 4026.12   18.32
 4032.46   18.14 4036.43   18.13 4064.97   17.93 4105.28   17.89 4113.38      18
 4156.15   19.16 4176.78   18.96 4229.24   18.97 4241.03   19.03 4246.99   19.05
 4269.35   19.13 4311.39   18.88 4357.43   18.27 4391.17   17.82 4399.41   18.05
 4430.19   18.34  4520.4   19.13 4536.27   18.92 4551.73   18.81 4605.02   19.79
 4609.21   20.05 4614.35   19.88 4629.13   20.95 4683.17   21.69 4699.75   21.68
 4745.78   21.58 4749.58   21.47 4756.92   21.38 4801.92   21.03  4857.7   19.94
 4867.06   20.61 4885.71   19.81 4909.72   19.87 4918.69   19.04 4927.46    18.9
    4938   17.68    4941   17.41    4941   16.76    4951   15.93    4956   13.95
 4978.77    8.03 5002.23    6.28 5002.92    5.12 5005.52    3.39  5016.2    5.15
 5017.41    5.93 5037.61    7.38 5060.11   11.79    5069   15.29    5079   16.12
 5090.29   17.01  5134.3   16.54 5137.95   16.49 5152.76   16.45 5168.02   16.95
 5206.76   17.24  5215.1   17.28 5263.32   17.61 5283.24   17.18 5322.51   19.27
  5348.8   18.86 5387.74   18.73 5418.61   18.39 5428.49      19 5450.51   18.85
 5450.63   18.84    5471   18.26 5478.93   18.31 5499.66   19.15 5514.37   18.29
 5533.02   19.41 5587.74   19.12 5600.03   19.31    5632   20.29 5632.57    20.3
 5645.59   20.27 5648.08   20.28 5674.18   19.29 5676.56   19.27 5681.25   19.24
 5720.33   19.74 5738.92   19.58 5743.69   19.54 5758.75   19.35 5759.15   19.35
  5781.7   19.75 5801.27   19.44 5806.28   19.34 5862.83   19.16 5875.21   19.06
 5877.26   19.26 5918.22   19.19 5920.97   19.21 5927.46   18.99
BR D #Mann= 4
 3418.41     .15 4909.72    .015 5090.29     .15 5676.56    .032
BC Design=,, 0 ,, 0 ,,,,,,
BC HTab HWMax=22.12

Type RM Length L Ch R = 1 ,166.985 ,81.33,83.3,100.19
XS GIS Cut Line= 6
     3199713.221    13782213.095     3198517.417    13783448.759
     3198425.463     13783747.61     3198334.396    13783904.468
     3198240.311    13783989.999     3198089.206    13784064.126
#Sta/Elev= 30
 3418.41   19.62 4000.24   19.25 4032.46   18.14 4105.28   17.89 4156.15   19.16
 4269.35   19.13 4391.17   17.82 4551.73   18.81 4683.17   21.69 4909.72   19.87
 4927.46    18.9    4951   15.93 4978.77    8.03 5002.23    6.28 5005.52    3.39
 5017.41    5.93 5037.61    7.38 5060.11   11.79    5069   15.29 5090.29   17.01
 5283.24   17.18 5322.51   19.27    5471   18.26 5499.66   19.15 5514.37   18.29
 5533.02   19.41 5587.74   19.12 5632.57    20.3 5676.56   19.27 5927.46   18.99
#Mann= 4 ,-1 , 0
 3418.41     .15       0 4909.72    .032       0 5090.29     .15       0
 5676.56    .032       0
Bank Sta=4909.72,5090.29
XS Rating Curve= 0
Exp/Cntr=0.5,0.3

Type RM Length L Ch R = 1 ,83.687  ,204.92,83.69,133.78
XS GIS Cut Line= 6
     3199655.733    13782157.461     3198446.594    13783406.905
     3198371.459    13783733.405      3198291.63    13783867.404
     3198200.397    13783947.233     3198060.696    13784009.956
#Sta/Elev= 30
 3408.18   17.66 3792.77   17.45 3888.33   12.64 3984.14   14.08    4149   13.06
 4185.65   14.41 4326.68   12.93 4441.97   13.73 4609.57   11.25 4643.62   13.34
  4708.6   10.88    4786   13.94 4903.22   12.75 4932.03    9.97 4963.81    1.93
 4970.09    1.87 4989.94    2.76 5006.47    7.43 5096.79   10.56 5194.33   10.86
 5221.71   13.16 5298.92    12.7 5368.54   10.09 5481.93   11.99 5498.33   10.34
 5550.71   10.25  5637.9   13.52 5690.51   12.17 5862.47   12.35 5912.27    13.9
#Mann= 3 , 0 , 0
 3408.18     .15       0 4903.22    .032       0 5096.79     .15       0
#Block Obstruct= 2 ,-1
 3706.48 4784.98   13.92 5218.43 5935.15   13.21
Bank Sta=4903.22,5096.79
XS Rating Curve= 0
Exp/Cntr=0.3,0.1

Chan Stop Cuts=-1

--- B104_04_00.g01 (geometry) ---

Geom Title=B104-04-00 June 2007
Program Version=3.11

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
River Reach=B104-04-00      ,B104-04-00_0001